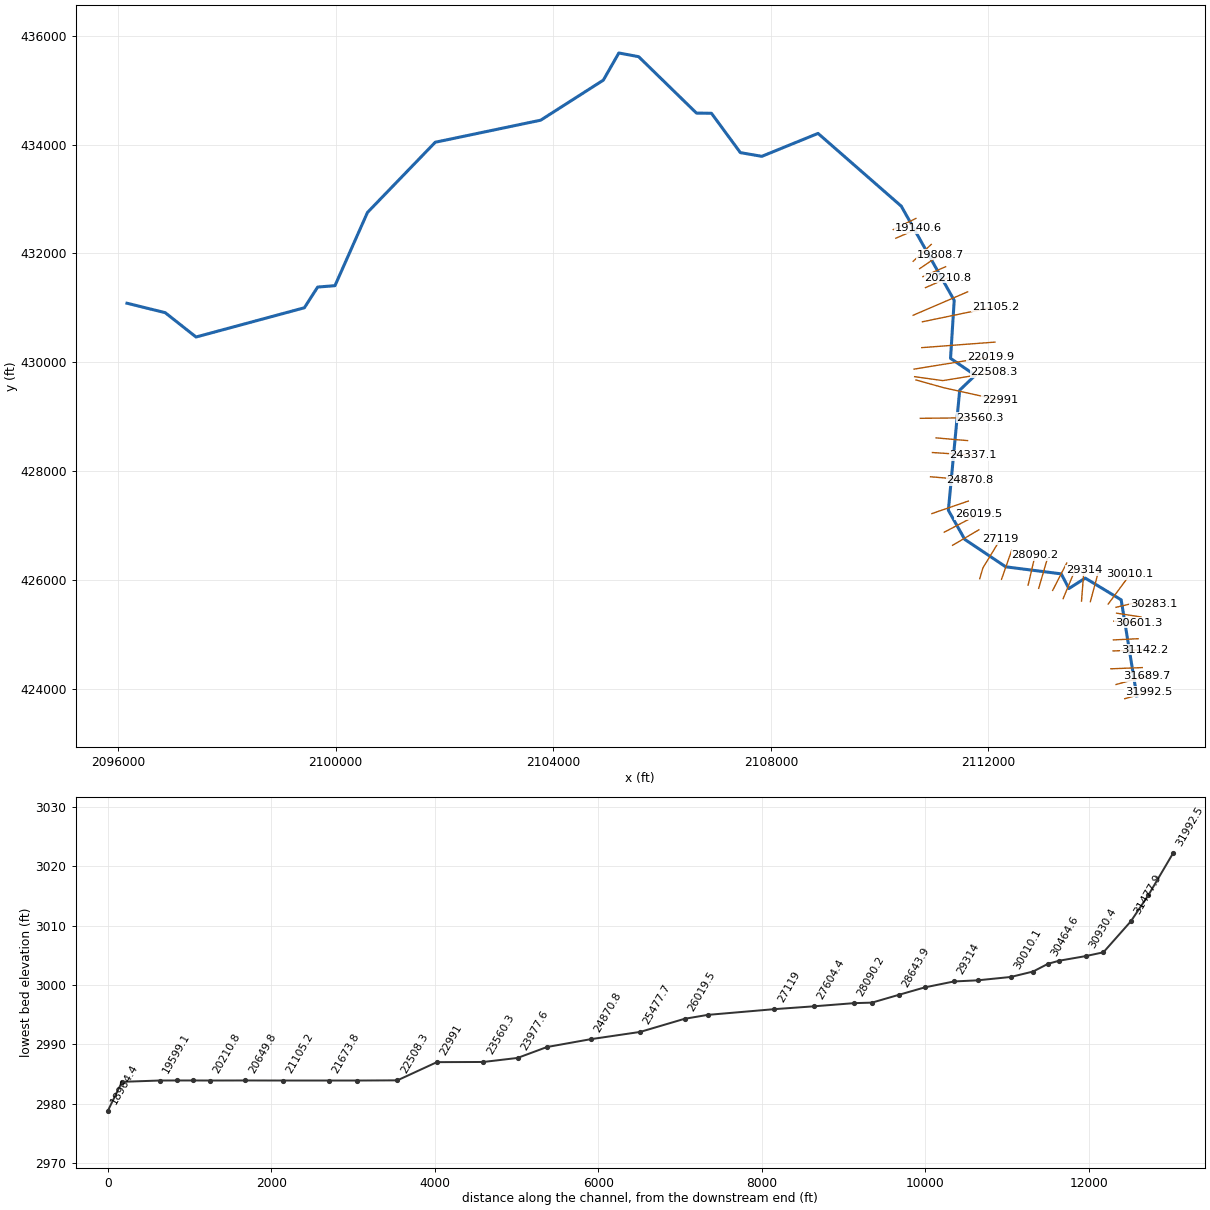
--- LitLaurCk.prj (project) ---

Proj Title=LitLaurCk
Current Plan=p01
Default Exp/Contr=0,0
English Units
Geom File=g01
Flow File=f01
Plan File=p01
BEGIN DESCRIPTION:
END DESCRIPTION:
DSS Export Rating Curves= 0
DSS Export Rating Curve Sorted= 0
DSS Export Volume Flow Curves= 0
DXF OffsetX= 0
DXF OffsetY= 0
DXF ScaleX= 0
DXF ScaleY= 0

--- LitLaurCk.p01 (plan) ---

Plan Title=Floodplain
Program Version=4.00
Geom File=g01
Flow File=f01
K Sum by GR=0
Std Step Tol=0.01
Critical Tol=0.01
Num of Std Step Trials=20
Max Error Tol=0.3
Flow Tol Ratio=0.001
Split Flow NTrial=30
Split Flow Tol=0.02
Split Flow Ratio=0.02
Log Output Level=0
Friction Slope Method=1
Unsteady Friction Slope Method=2
Unsteady Bridges Friction Slope Method=1
Global Log Level=0
CheckData=False
Run HTab=0
Run UNet=0
Run PostProcess=0
UNET Theta=0
UNET Theta Warmup=0
UNET ZTol=0
UNET ZSATol=0
UNET MxIter=0
UNET MaxInSteps=0
UNET DtIC=0
UNET DtMin=0
UNET MaxCRTS=0
UNET WFStab=0
UNET SFStab=0
UNET WFX=0
UNET SFX=0
UNET DSS MLevel=0
UNET DZMax Abort=0
UNET Convert EG Bridges=0
UNET Use Existing IB Tables=0
UNET Froude Limit=0
UNET Froude Power=0
Write IC File=0
Echo Input=False
Echo Output=False
Write Detailed=0

--- LitLaurCk.f01 (steady flow) ---

Flow Title=NFF Regression Equation
Program Version=4.00
Number of Profiles=1
Profile Names=P100yr
River Rch & RM=LitLaurCk,Main      ,31992.5
578.2807
River Rch & RM=LitLaurCk,Main      ,30283.1
608.2601
River Rch & RM=LitLaurCk,Main      ,29602.4
703.7758
River Rch & RM=LitLaurCk,Main      ,27604.4
736.1474
River Rch & RM=LitLaurCk,Main      ,24870.8
816.5054
River Rch & RM=LitLaurCk,Main      ,20649.8
887.7087
River Rch & RM=LitLaurCk,Main      ,20210.8
996.3252
River Rch & RM=LitLaurCk,Main      ,16762.7
1078.020
River Rch & RM=LitLaurCk,Main      ,16481.2
1198.597
River Rch & RM=LitLaurCk,Main      ,11576.9
1265.195
River Rch & RM=LitLaurCk,Main      ,11088.8
1460.042
River Rch & RM=LitLaurCk,Main      ,6570.2
1575.408
River Rch & RM=LitLaurCk,Main      ,6010.9
2091.256
River Rch & RM=LitLaurCk,Main      ,3013.5
2318.702
River Rch & RM=LitLaurCk,Main      ,27.9
2420.492
Boundary for River Rch & Prof#=LitLaurCk,Main      ,1
Up Type=0
Dn Type=3
Dn Slope=0.02672

--- LitLaurCk.g01 (geometry) ---

Geom Title=USGS 10m DEM
Program Version=4.00

River Reach=LitLaurCk       ,Main
Reach XY= 30
     2114726.547      423871.573     2114439.784      425635.318
     2113779.359      426034.199     2113478.578      425842.792
     2113337.953      426112.323     2112317.749      426241.723
     2111564.179      426745.867     2111263.256      427280.201
      2111471.41       429487.61     2111757.699      429761.072
     2111303.136      430071.895     2111370.518      431136.203
     2110397.754      432867.107     2108867.772      434204.044
     2107834.255      433783.145      2107439.72      433851.057
     2106908.573      434573.704     2106632.355      434577.811
     2105569.582      435613.886     2105206.083      435681.658
     2104920.624      435182.616     2103769.342      434447.222
     2101830.882      434041.804     2100585.332      432752.101
     2099987.715       431406.95     2099669.397      431381.279
      2099425.29      431000.932     2097434.042       430463.74
     2096867.023      430910.908      2096164.83       431084.37

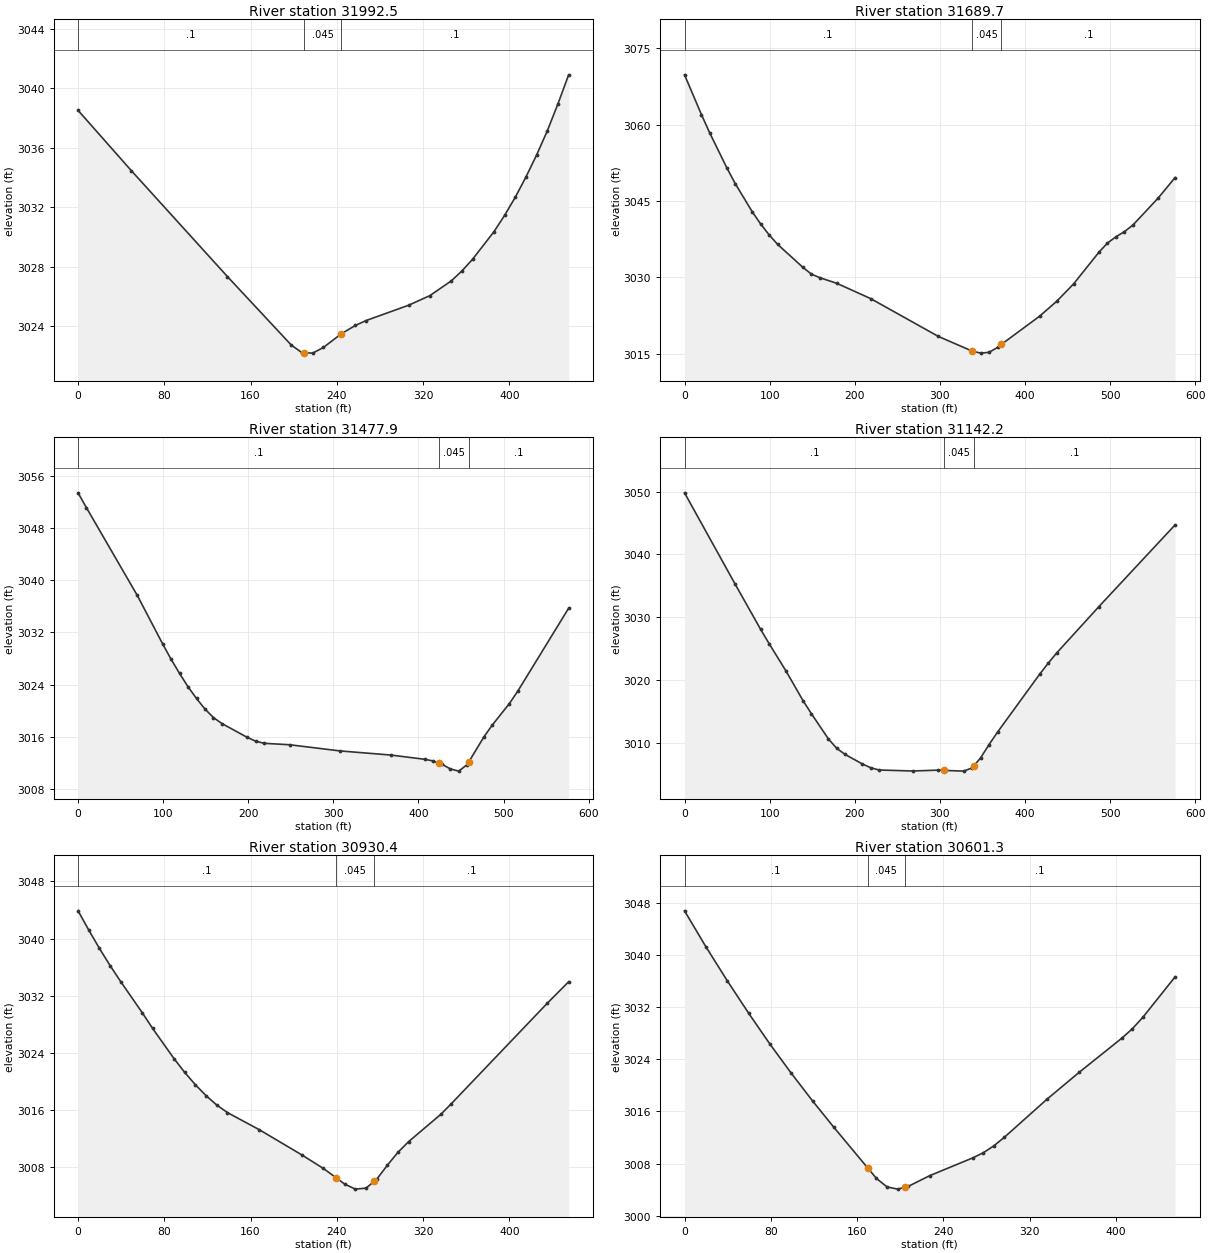
Type RM Length L Ch R = 1 ,31992.5 ,299.1,302.8,303.3
XS GIS Cut Line= 3
      2114505.08      423818.576     2114723.795      423881.187
      2114942.51      423943.798
#Sta/Elev= 24
       0 3038.52    49.5 3034.46   138.5 3027.35   197.8 3022.74   207.7 3022.23
   209.33022.225   217.6  3022.2   227.5 3022.58   244.33023.508   257.2 3024.06
   267.1 3024.39   306.6 3025.42   326.4 3026.07   346.2 3027.06   356.1 3027.73
     366 3028.52   385.8 3030.37   395.6 3031.46   405.5 3032.68   415.4 3034.04
   425.3 3035.52   435.2 3037.14   445.1 3038.96     455 3040.91
#Mann= 3 , 0 , 0
       0      .1       0   209.3    .045       0   244.3      .1       0
Bank Sta=209.3,244.3
XS Rating Curve= 0 ,0
Exp/Cntr=0.3,0.1

Type RM Length L Ch R = 1 ,31689.7 ,217.1,211.8,206.5
XS GIS Cut Line= 2
     2114345.308      424079.861      2114901.32      424232.102
#Sta/Elev= 30
       0 3069.76    19.9 3061.94    29.8 3058.28    49.7  3051.5    59.6 3048.39
    79.5 3042.89    89.4 3040.49    99.4 3038.34   109.3 3036.48   139.2 3031.94
   149.1 3030.63     159 3029.92   178.9 3028.82   218.7 3025.82   298.2  3018.4
   337.43015.552   347.9 3015.11   357.8 3015.26   367.8 3016.22   372.43016.829
   417.4 3022.38   437.3 3025.28   457.2  3028.7     487 3034.93     497 3036.72
   506.9 3037.95   516.8 3038.95   526.8 3040.24   556.6 3045.56   576.5 3049.59
#Mann= 3 , 0 , 0
       0      .1       0   337.4    .045       0   372.4      .1       0
Bank Sta=337.4,372.4
XS Rating Curve= 0 ,0
Exp/Cntr=0.3,0.1

Type RM Length L Ch R = 1 ,31477.9 ,335.9,335.7,335.4
XS GIS Cut Line= 2
     2114250.424      424368.148     2114826.464      424390.604
#Sta/Elev= 30
       0 3053.36     9.9 3051.07    69.6 3037.65    99.4 3030.23   109.3 3027.88
   119.3  3025.7   129.2 3023.67   139.2 3021.87   149.1 3020.26     159 3018.96
     169 3018.04   198.8 3015.92   208.7 3015.34   218.7 3015.01   248.5 3014.79
   308.1 3013.84   367.8 3013.21   407.5 3012.56   417.4  3012.3     424 3011.99
   427.4 3011.83   437.3  3011.1   447.3 3010.75   457.2 3011.74     4593012.118
   477.1 3016.03     487 3017.84   506.9  3021.1   516.8 3023.01   576.5 3035.69
#Mann= 3 , 0 , 0
       0      .1       0     424    .045       0     459      .1       0
Bank Sta=424,459
XS Rating Curve= 0 ,0
Exp/Cntr=0.3,0.1

Type RM Length L Ch R = 1 ,31142.2 ,211.5,211.8,212.2
XS GIS Cut Line= 2
     2114290.956      424696.206     2114867.009      424718.332
#Sta/Elev= 27
       0 3049.81    59.6 3035.25    89.4 3028.09    99.4 3025.81   119.3 3021.44
   139.2 3016.75   149.1 3014.66     169 3010.66   178.9 3009.14   188.8 3008.17
   208.7 3006.68   218.7 3006.06   228.6  3005.7   268.4 3005.54   298.2 3005.68
   304.93005.639     328 3005.52   337.9 3006.03   339.93006.348   347.9 3007.62
   357.8 3009.73   367.8 3011.72   417.4 3020.96   427.4  3022.7   437.3 3024.32
     487 3031.71   576.5 3044.71
#Mann= 3 , 0 , 0
       0      .1       0   304.9    .045       0   339.9      .1       0
Bank Sta=304.9,339.9
XS Rating Curve= 0 ,0
Exp/Cntr=0.3,0.1

Type RM Length L Ch R = 1 ,30930.4 ,331.4,329.1,326.8
XS GIS Cut Line= 2
     2114297.257      424898.849     2114751.706      424921.222
#Sta/Elev= 29
       0 3043.89     9.9  3041.2    19.8 3038.63    29.7 3036.22    39.6 3033.96
    59.4 3029.64    69.2  3027.4      89 3023.18    98.9 3021.25   108.8 3019.52
   118.7 3017.99   128.6 3016.68   138.5 3015.62   168.2 3013.21   207.7 3009.67
   227.5 3007.79   239.63006.456   247.3  3005.6   257.2 3004.89   267.1 3005.03
   274.63005.969     277 3006.27   286.8 3008.23   296.7 3010.05   306.6 3011.55
   336.3 3015.35   346.2 3016.86   435.2 3030.94     455 3033.95
#Mann= 3 , 0 , 0
       0      .1       0   239.6    .045       0   274.6      .1       0
Bank Sta=239.6,274.6
XS Rating Curve= 0 ,0
Exp/Cntr=0.3,0.1

Type RM Length L Ch R = 1 ,30601.3 ,139,136.7,134.4
XS GIS Cut Line= 2
     2114303.859      425243.216     2114758.191      425218.561
#Sta/Elev= 25
       0 3046.73    19.8 3041.23    39.6 3036.03    59.4 3031.06    79.1 3026.34
    98.9 3021.88   118.7 3017.62   138.5 3013.57   169.73007.383     178 3005.74
   187.9 3004.43   197.8  3004.1   204.73004.407   207.7 3004.54   227.5 3006.17
   267.1 3008.87     277 3009.66   286.8 3010.72   296.7 3012.05   336.3 3017.89
     366 3021.99   405.5 3027.21   415.4 3028.67   425.3 3030.46     455 3036.62
#Mann= 3 , 0 , 0
       0      .1       0   169.7    .045       0   204.7      .1       0
Bank Sta=169.7,204.7
XS Rating Curve= 0 ,0
Exp/Cntr=0.3,0.1

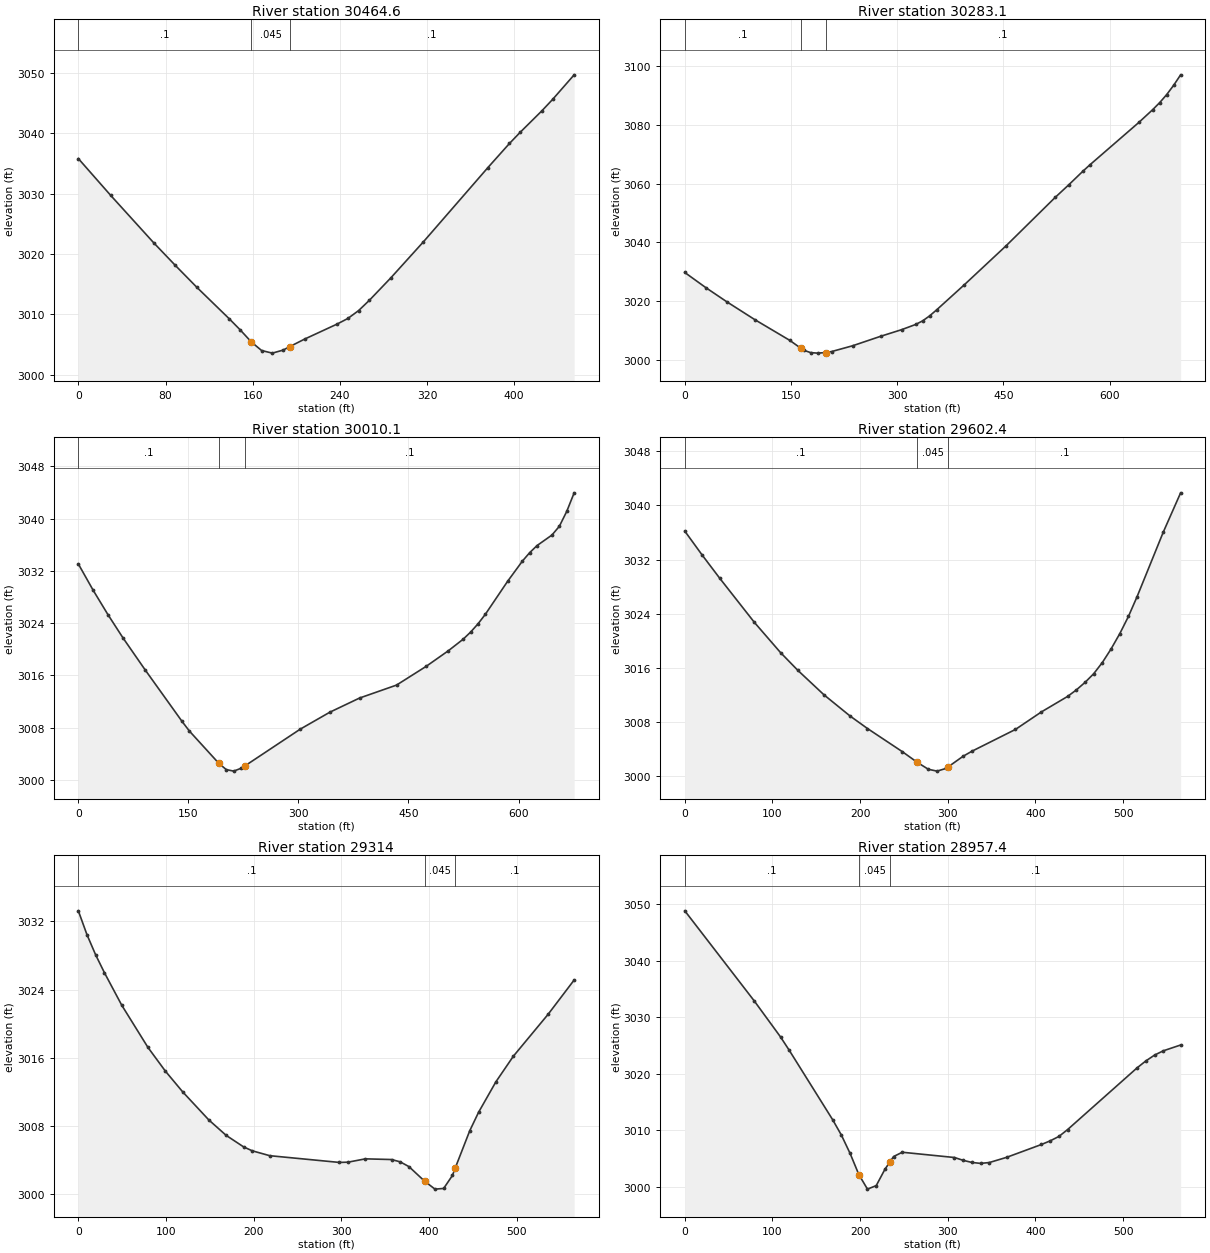
Type RM Length L Ch R = 1 ,30464.6 ,172.6,181.6,190.5
XS GIS Cut Line= 3
     2114354.996      425390.077     2114579.862      425355.556
     2114804.727      425321.035
#Sta/Elev= 25
       0 3035.82    29.7 3029.72    69.2 3021.86      89 3018.12   108.8 3014.48
   138.5 3009.27   148.4 3007.46   158.83005.425   168.2 3004.01     178 3003.58
   187.9 3004.08   193.8 3004.64   207.7 3005.91   237.4 3008.39   247.3 3009.32
   257.2 3010.63   267.1 3012.34   286.8 3016.06   316.5 3021.99   375.9 3034.34
   395.6 3038.32   405.5 3040.18   425.3 3043.72   435.2 3045.62     455  3049.7
#Mann= 3 , 0 , 0
       0      .1       0   158.8    .045       0   193.8      .1       0
Bank Sta=158.8,193.8
XS Rating Curve= 0 ,0
Exp/Cntr=0.3,0.1

Type RM Length L Ch R = 1 ,30283.1 ,257,273,288.9
XS GIS Cut Line= 3
     2114344.203      425497.758     2114661.502      425572.621
     2115035.444      425553.657
#Sta/Elev= 30
       0 3029.74    29.6  3024.6    59.3 3019.77    98.8  3013.7   148.2 3006.64
   163.8 3003.96     168 3003.26   177.8 3002.45   187.7 3002.28   198.83002.469
   207.5 3002.82   237.1 3004.79   276.6 3008.01   306.2 3010.26     326 3012.03
   335.9 3013.26   345.7 3014.94   355.6 3016.98     395 3025.59   454.1 3038.89
   523.1 3055.28   542.8 3059.69   562.5 3064.26   572.3 3066.41   641.3 3080.82
     661  3085.2   670.9  3087.6   680.7 3090.31   690.6  3093.5   700.4 3097.05
#Mann= 3 , 0 , 0
       0      .1       0   163.8    .045       0   198.8      .1       0
Bank Sta=163.8,198.8
XS Rating Curve= 0 ,0
Exp/Cntr=0.3,0.1

Type RM Length L Ch R = 1 ,30010.1 ,399.1,407.7,416.2
XS GIS Cut Line= 2
     2114201.368      425557.467     2114602.779      426101.074
#Sta/Elev= 30
       0 3033.05    20.2 3029.03    40.3 3025.31    60.5  3021.8    90.8 3016.89
   141.2 3008.99   151.3  3007.5   191.6 3002.54   201.7 3001.59   211.8 3001.36
   221.9  3001.8   226.63002.126   302.6 3007.79   342.9 3010.38   383.3 3012.54
   433.7 3014.52     474 3017.38   504.3 3019.77   524.5 3021.54   534.6 3022.62
   544.6 3023.87   554.7 3025.34     585 3030.38   605.2 3033.48   615.2 3034.78
   625.3 3035.87   645.5 3037.47   655.6 3038.81   665.7 3041.09   675.8 3043.93
#Mann= 3 , 0 , 0
       0      .1       0   191.6    .045       0   226.6      .1       0
Bank Sta=191.6,226.6
XS Rating Curve= 0 ,0
Exp/Cntr=0.3,0.1

Type RM Length L Ch R = 1 ,29602.4 ,283,288.4,293.9
XS GIS Cut Line= 2
     2113873.188      425601.986     2114020.197      426148.282
#Sta/Elev= 30
       0 3036.21    19.8 3032.68    39.7 3029.28    79.4 3022.74   109.2 3018.29
     129 3015.66   158.8 3012.05   188.6 3008.92   208.4 3007.08   248.1 3003.67
   265.4 3002.07   277.9 3001.06   287.8 3000.79   297.8 3001.18   300.43001.411
   317.6 3002.99   327.5 3003.72   377.2 3006.94   406.9 3009.53   436.7 3011.81
   446.6 3012.76   456.6 3013.88   466.5 3015.16   476.4 3016.82   486.3 3018.81
   496.3 3021.08   506.2 3023.63   516.1 3026.56   545.9 3036.06   565.7 3041.86
#Mann= 3 , 0 , 0
       0      .1       0   265.4    .045       0   300.4      .1       0
Bank Sta=265.4,300.4
XS Rating Curve= 0 ,0
Exp/Cntr=0.3,0.1

Type RM Length L Ch R = 1 ,29314   ,364.7,356.7,348.6
XS GIS Cut Line= 2
     2113710.913      425612.964     2113754.431      426177.019
#Sta/Elev= 30
       0 3033.23     9.9 3030.42    19.8 3028.06    29.8 3025.97    49.6 3022.15
    79.4 3017.22    99.2 3014.45   119.1    3012   148.9 3008.71   168.7  3006.9
   188.6 3005.55   198.5 3005.09   218.4 3004.52   297.8 3003.73   307.7 3003.76
   327.5 3004.15   357.3 3004.07   367.2  3003.8   377.2 3003.24   395.1 3001.53
   406.9  3000.6   416.8 3000.68   426.8  3002.2   430.1  3003.1   446.6 3007.45
   456.6  3009.6   476.4 3013.18   496.3 3016.18     536  3021.1   565.7 3025.12
#Mann= 3 , 0 , 0
       0      .1       0   395.1    .045       0   430.1      .1       0
Bank Sta=395.1,430.1
XS Rating Curve= 0 ,0
Exp/Cntr=0.3,0.1

Type RM Length L Ch R = 1 ,28957.4 ,316.3,313.4,311.7
XS GIS Cut Line= 2
     2113372.395      425656.443     2113589.804      426178.731
#Sta/Elev= 30
       0  3048.8    79.4 3032.84   109.2 3026.51   119.1 3024.16   168.7 3011.87
   178.6 3009.17   188.6 3005.91   198.5  3002.2   199.13002.042   208.4  2999.6
   218.4 3000.22   228.3  3003.1   234.13004.424   238.2 3005.36   248.1 3006.12
   307.7 3005.19   317.6 3004.69   327.5 3004.32   337.4 3004.15   347.4  3004.3
   367.2 3005.22   406.9 3007.49   416.8 3008.13   426.8 3008.91   436.7 3010.12
   516.1 3021.05     526 3022.26     536  3023.3   545.9 3024.05   565.7 3025.08
#Mann= 3 , 0 , 0
       0      .1       0   199.1    .045       0   234.1      .1       0
Bank Sta=199.1,234.1
XS Rating Curve= 0 ,0
Exp/Cntr=0.3,0.1

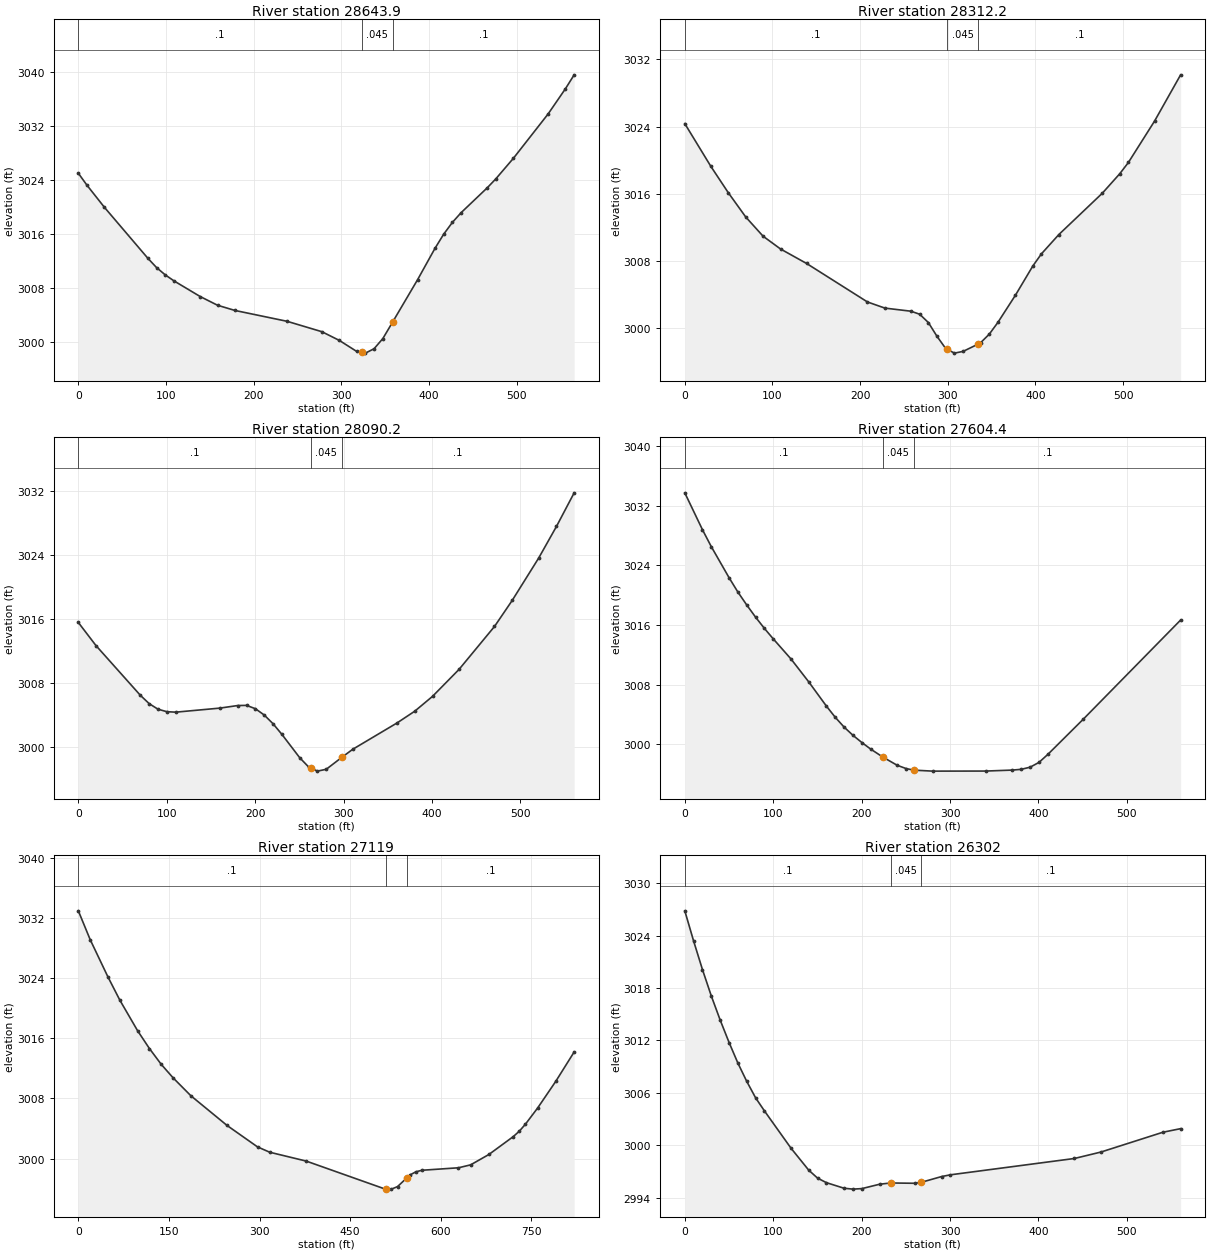
Type RM Length L Ch R = 1 ,28643.9 ,325.7,331.7,336.6
XS GIS Cut Line= 2
     2113180.371      425808.552     2113438.646      426311.886
#Sta/Elev= 30
       0 3024.99     9.9 3023.21    29.8 3019.94    79.4 3012.39    89.3 3011.02
    99.2 3009.94   109.2 3009.05     139 3006.74   158.8 3005.45   178.6 3004.68
   238.2 3003.07   277.9 3001.53   297.8 3000.24   317.6 2998.61   323.72998.456
   327.5 2998.36   337.4 2999.01   347.4 3000.51   358.73002.984   387.1 3009.24
   406.9 3013.87   416.8 3015.96   426.8 3017.72   436.7 3019.15   466.5 3022.83
   476.4 3024.17   496.3 3027.19     536 3033.77   555.8 3037.51   565.7 3039.56
#Mann= 3 , 0 , 0
       0      .1       0   323.7    .045       0   358.7      .1       0
Bank Sta=323.7,358.7
XS Rating Curve= 0 ,0
Exp/Cntr=0.3,0.1

Type RM Length L Ch R = 1 ,28312.2 ,220.8,222.1,223.3
XS GIS Cut Line= 2
     2112923.594      425846.692     2113082.045       426389.78
#Sta/Elev= 30
       0 3024.35    29.8 3019.25    49.6 3016.13    69.5 3013.24    89.3 3010.95
   109.2 3009.43     139  3007.7   208.4 3003.12   228.3 3002.39     258 3002.02
     268 3001.66   277.9 3000.67   287.8 2999.02   297.8 2997.56   299.52997.469
   307.7 2997.03   317.6 2997.24   334.52998.096   337.4 2998.26   347.4 2999.29
   357.3  3000.7   377.2 3003.92     397 3007.39   406.9 3008.85   426.8 3011.15
   476.4 3016.07   496.3 3018.39   506.2 3019.74     536 3024.66   565.7 3030.16
#Mann= 3 , 0 , 0
       0      .1       0   299.5    .045       0   334.5      .1       0
Bank Sta=299.5,334.5
XS Rating Curve= 0 ,0
Exp/Cntr=0.3,0.1

Type RM Length L Ch R = 1 ,28090.2 ,489.7,485.8,480.4
XS GIS Cut Line= 2
     2112729.287      425905.834     2112857.064       426451.87
#Sta/Elev= 30
       0 3015.57      20 3012.67    70.1 3006.45    80.1  3005.4    90.1  3004.7
   100.1 3004.39   110.2 3004.33   160.2 3004.84   180.2 3005.16   190.3 3005.18
   200.3 3004.76   210.3 3003.97   220.3 3002.87   230.3 3001.54   250.4 2998.62
   260.4 2997.47   262.92997.337   270.4 2996.94   280.4 2997.17   297.92998.657
   310.4 2999.68   360.5 3002.98   380.5 3004.45   400.6 3006.31   430.6 3009.69
   470.7 3015.07   490.7 3018.33   520.7 3023.65   540.8 3027.61   560.8 3031.82
#Mann= 3 , 0 , 0
       0      .1       0   262.9    .045       0   297.9      .1       0
Bank Sta=262.9,297.9
XS Rating Curve= 0 ,0
Exp/Cntr=0.3,0.1

Type RM Length L Ch R = 1 ,27604.4 ,491.1,485.4,475.3
XS GIS Cut Line= 2
     2112240.423      426012.394     2112425.616      426541.719
#Sta/Elev= 30
       0 3033.71      20 3028.76      30 3026.49    50.1 3022.33    60.1  3020.4
    70.1 3018.67    80.1 3017.04    90.1 3015.53   100.1 3014.13   120.2 3011.43
   140.2 3008.37   160.2 3005.12   170.2 3003.62   180.2 3002.31   190.3  3001.2
   200.3 3000.24   210.3 2999.36   224.12998.285   240.3 2997.19   250.4 2996.75
   259.12996.541   280.4 2996.41   340.5 2996.42   370.5 2996.55   380.5 2996.65
   390.6 2996.94   400.6 2997.58   410.6 2998.65   450.6 3003.36   560.8 3016.66
#Mann= 3 , 0 , 0
       0      .1       0   224.1    .045       0   259.1      .1       0
Bank Sta=224.1,259.1
XS Rating Curve= 0 ,0
Exp/Cntr=0.3,0.1

Type RM Length L Ch R = 1 ,27119   ,829.3,817,818.3
XS GIS Cut Line= 3
     2111840.248      426023.605     2111897.851      426221.395
     2112218.089      426746.384
#Sta/Elev= 30
       0 3032.96    19.6 3029.13      49 3024.17    68.7 3021.08    98.1 3017.01
   117.7 3014.64   137.3 3012.53     157 3010.73   186.4 3008.35   246.3  3004.4
   296.7 3001.55   316.9 3000.84   377.4 2999.66   508.4 2995.93   508.9 2995.93
   518.5 2995.93   528.6 2996.27   543.92997.427   548.8  2997.8   558.8 2998.23
   568.9 2998.44   629.4 2998.77   649.6 2999.16   679.8 3000.54   720.2 3002.92
   730.2 3003.64   740.3 3004.57   760.5 3006.72   790.7 3010.29     821 3014.18
#Mann= 3 , 0 , 0
       0      .1       0   508.9    .045       0   543.9      .1       0
Bank Sta=508.9,543.9
XS Rating Curve= 0 ,0
Exp/Cntr=0.3,0.1

Type RM Length L Ch R = 1 ,26302   ,283.7,282.5,281.3
XS GIS Cut Line= 2
     2111340.715      426636.841      2111823.78      426921.674
#Sta/Elev= 27
       0 3026.85      10 3023.38      20 3020.11      30 3017.09    40.1 3014.31
    50.1 3011.76    60.1 3009.39    70.1  3007.3    80.1 3005.42    90.1 3003.92
   120.2 2999.64   140.2 2997.13   150.2 2996.22   160.2  2995.7   180.2 2995.06
   190.3 2994.96   200.3 2995.02   220.3 2995.52   232.72995.665   260.4 2995.63
   267.72995.747   290.4  2996.4   300.4  2996.6   440.6 2998.47   470.7 2999.21
   540.8 3001.48   560.8 3001.89
#Mann= 3 , 0 , 0
       0      .1       0   232.7    .045       0   267.7      .1       0
Bank Sta=232.7,267.7
XS Rating Curve= 0 ,0
Exp/Cntr=0.3,0.1

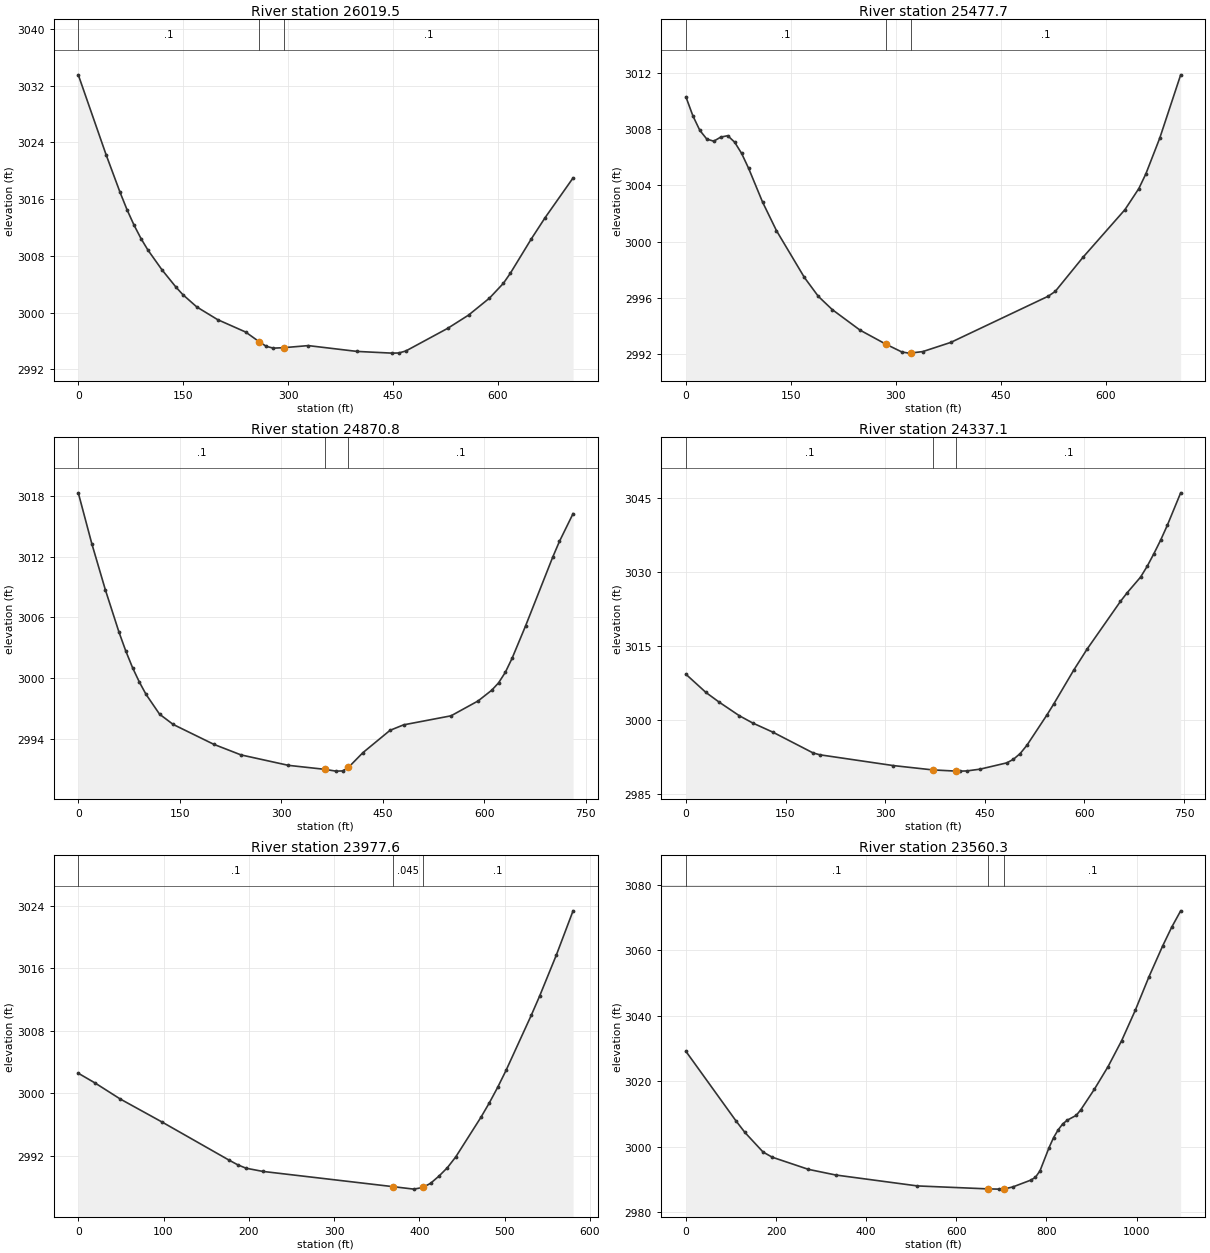
Type RM Length L Ch R = 1 ,26019.5 ,569.5,541.9,535.1
XS GIS Cut Line= 2
     2111187.081      426877.588     2111813.354       427206.31
#Sta/Elev= 30
       0 3033.52    39.8 3022.25    59.8 3016.94    69.7 3014.51    79.7 3012.34
    89.7 3010.44    99.6 3008.82   119.5 3006.06   139.5 3003.62   149.4 3002.55
   169.4 3000.81   199.2 2999.02   239.1 2997.28   258.92995.888   268.9 2995.25
   278.9    2995   293.9 2995.07   328.8 2995.36   398.5 2994.54   448.3  2994.3
   458.2 2994.32   468.2  2994.6     528 2997.79   557.9 2999.66   587.8 3002.05
   607.7 3004.14   617.6 3005.55   647.5 3010.38   667.4  3013.4   707.3 3018.99
#Mann= 3 , 0 , 0
       0      .1       0   258.9    .045       0   293.9      .1       0
Bank Sta=258.9,293.9
XS Rating Curve= 0 ,0
Exp/Cntr=0.3,0.1

Type RM Length L Ch R = 1 ,25477.7 ,615.9,606.9,597.5
XS GIS Cut Line= 2
     2110960.649      427219.868     2111629.495      427449.913
#Sta/Elev= 30
       0 3010.28      10 3008.93    19.9  3007.9    29.9 3007.28    39.8 3007.13
    49.8 3007.42    59.8 3007.52    69.7 3007.06    79.7 3006.26    89.7  3005.2
   109.6 3002.81   129.5 3000.78   169.4 2997.46   189.3 2996.12   209.2 2995.18
     249 2993.72   286.1 2992.72   308.8 2992.17   318.8 2992.09   321.12992.095
   338.7  2992.2   378.6 2992.85     518 2996.13     528 2996.47   567.8  2998.9
   627.6 3002.27   647.5 3003.77   657.5 3004.81   677.4 3007.35   707.3 3011.84
#Mann= 3 , 0 , 0
       0      .1       0   286.1    .045       0   321.1      .1       0
Bank Sta=286.1,321.1
XS Rating Curve= 0 ,0
Exp/Cntr=0.3,0.1

Type RM Length L Ch R = 1 ,24870.8 ,533.9,533.7,531.9
XS GIS Cut Line= 2
     2110934.362      427896.297     2111663.237      427834.559
#Sta/Elev= 30
       0 3018.28      20 3013.27    40.1 3008.71    60.1 3004.57    70.1 3002.72
    80.2 3001.06    90.2 2999.65   100.2 2998.42   120.2 2996.47   140.3 2995.46
   200.4  2993.5   240.5 2992.46   310.6 2991.43   364.32991.038   380.8 2990.86
   390.8 2990.88   399.3 2991.22   420.8 2992.68   460.9 2994.88     481 2995.42
   551.1 2996.31   591.2 2997.78   611.2 2998.83   621.3 2999.55   631.3 3000.59
   641.3 3001.97   661.3 3005.17   701.4 3011.94   711.4  3013.5   731.5 3016.23
#Mann= 3 , 0 , 0
       0      .1       0   364.3    .045       0   399.3      .1       0
Bank Sta=364.3,399.3
XS Rating Curve= 0 ,0
Exp/Cntr=0.3,0.1

Type RM Length L Ch R = 1 ,24337.1 ,361.8,359.5,360.7
XS GIS Cut Line= 2
     2110969.881      428341.484     2111713.163      428292.971
#Sta/Elev= 30
       0 3009.19    30.2 3005.49    50.3 3003.51    80.5 3000.77   100.7 2999.29
   130.8 2997.45   191.2 2993.25   201.3 2992.86     312 2990.67   371.52989.789
   406.52989.546   412.7 2989.54   422.8 2989.58   442.9 2989.94   483.2 2991.22
   493.2 2991.95   503.3 2993.11   513.4 2994.78   543.6 3000.94   553.6 3003.11
   583.8    3010   603.9 3014.26   654.3 3023.97   664.3  3025.7   684.5 3028.88
   694.5 3031.08   704.6 3033.64   714.7 3036.37   724.7 3039.36   744.9 3045.97
#Mann= 3 , 0 , 0
       0      .1       0   371.5    .045       0   406.5      .1       0
Bank Sta=371.5,406.5
XS Rating Curve= 0 ,0
Exp/Cntr=0.3,0.1

Type RM Length L Ch R = 1 ,23977.6 ,416.1,417.3,418.4
XS GIS Cut Line= 3
     2111037.105       428610.99     2111389.972      428579.729
     2111615.386      428560.945
#Sta/Elev= 23
       0 3002.55    19.7  3001.3    49.2 2999.25    98.4 2996.29   177.1  2991.4
     187 2990.82   196.8 2990.38   216.5 2989.97   369.12988.018   393.6  2987.7
   404.12987.911   413.3 2988.45   423.1 2989.37   432.9 2990.44   442.8 2991.83
   472.3  2996.9   482.1 2998.74   491.9 3000.73   501.8 3002.92   531.3 3009.96
   541.1 3012.42   560.8  3017.7   580.4 3023.36
#Mann= 3 , 0 , 0
       0      .1       0   369.1    .045       0   404.1      .1       0
Bank Sta=369.1,404.1
XS Rating Curve= 0 ,0
Exp/Cntr=0.3,0.1

Type RM Length L Ch R = 1 ,23560.3 ,580.8,569.3,557.4
XS GIS Cut Line= 2
     2110747.122      428969.668     2111844.971      428982.149
#Sta/Elev= 30
       0 3029.16   110.8 3007.95   130.9 3004.36   171.2 2998.37   191.4 2996.79
     272 2993.06   332.4 2991.34   513.7    2988     671 2987.09     695 2987.02
     7062987.067   725.2 2987.68   765.5 2989.78   775.6 2990.65   785.7  2992.6
   805.8  2999.7   815.9 3002.78     826 3005.13     836 3006.93   846.1 3008.09
   866.2 3009.58   876.3 3011.29   906.5 3017.58   936.8 3024.49     967 3032.44
   997.2 3041.71  1027.4 3051.91  1057.6 3061.28  1077.8 3067.06  1097.9 3072.11
#Mann= 3 , 0 , 0
       0      .1       0     671    .045       0     706      .1       0
Bank Sta=671,706
XS Rating Curve= 0 ,0
Exp/Cntr=0.3,0.1

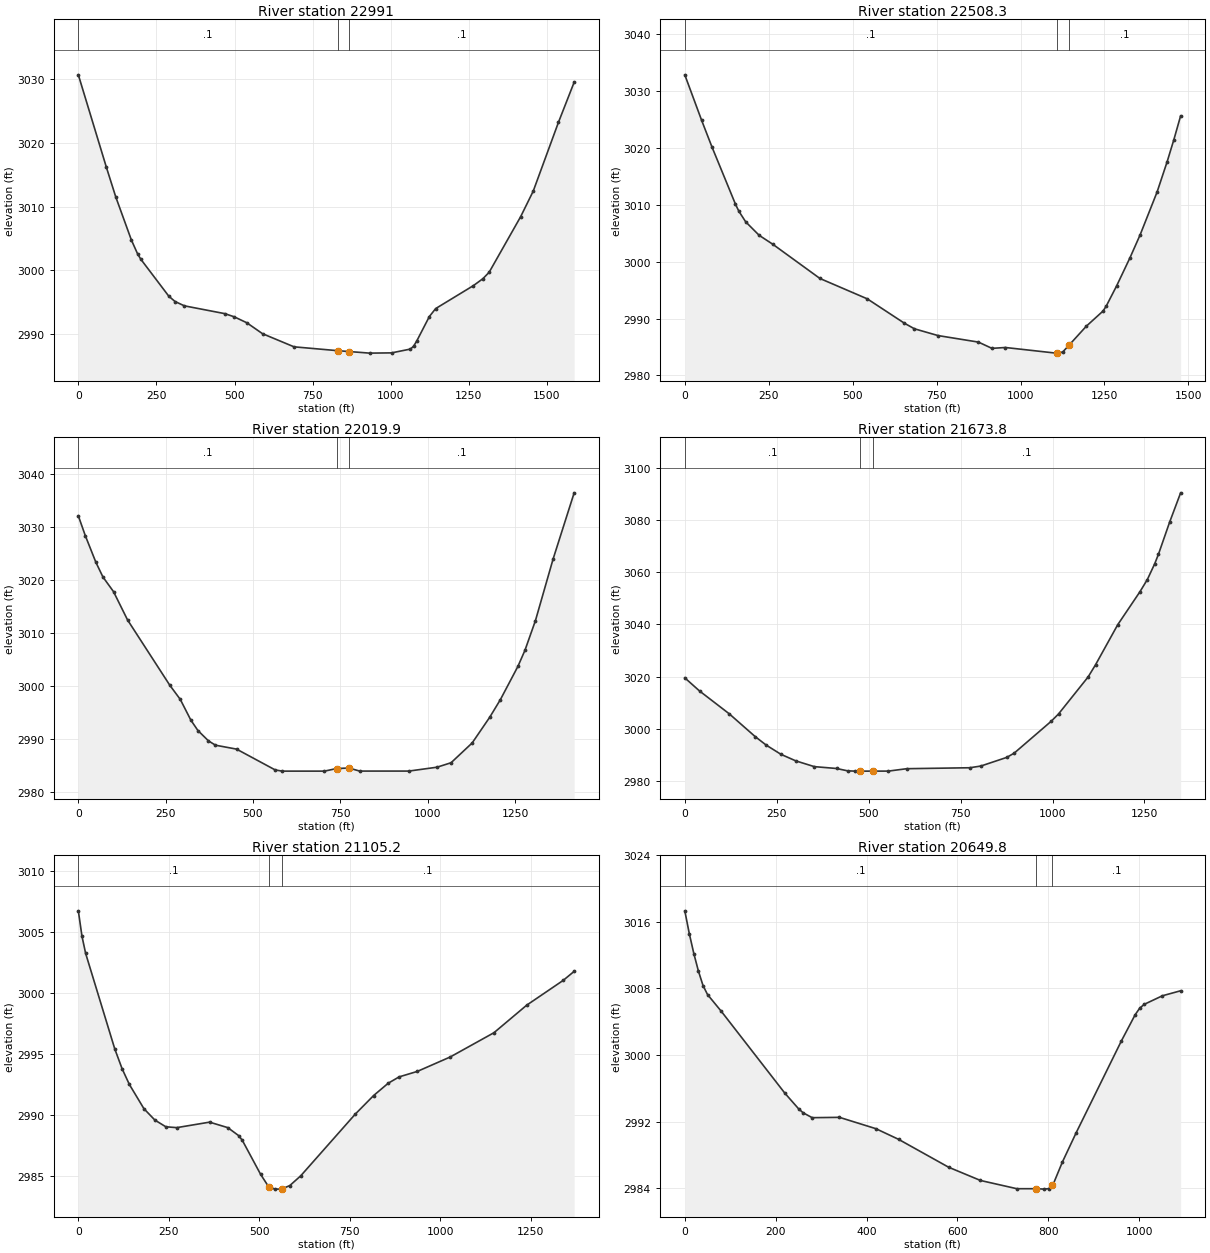
Type RM Length L Ch R = 1 ,22991   ,469.2,482.7,494.7
XS GIS Cut Line= 3
     2110667.244      429675.284     2111176.891      429532.174
     2112210.013      429304.116
#Sta/Elev= 30
       0 3030.72    89.9 3016.18   119.8 3011.54   169.8 3004.77   189.8 3002.58
   199.8 3001.76   289.6 2995.94   309.6  2995.1   339.6 2994.42   469.4 2993.19
   499.4 2992.69   539.4 2991.76   589.8 2990.04   690.6 2987.98   831.12987.371
   866.12987.243   932.4 2986.99  1002.9 2987.03  1063.4 2987.63  1073.5 2988.09
  1083.6 2988.91  1123.8 2992.74    1144 2993.99  1264.9  2997.6  1295.1 2998.68
  1315.3  2999.7  1416.1 3008.43  1456.4 3012.45    1537 3023.24  1587.4 3029.56
#Mann= 3 , 0 , 0
       0      .1       0   831.1    .045       0   866.1      .1       0
Bank Sta=831.1,866.1
XS Rating Curve= 0 ,0
Exp/Cntr=0.3,0.1

Type RM Length L Ch R = 1 ,22508.3 ,489.6,488.4,487.9
XS GIS Cut Line= 3
     2110642.974      429734.857     2111161.366      429662.733
     2112102.505      429815.391
#Sta/Elev= 30
       0 3032.88    50.3 3024.85    80.5 3020.25     151 3010.11     161 3008.89
   181.2 3007.03   221.4 3004.65   261.7 3003.09   402.6 2997.05   543.5 2993.47
   653.9 2989.19     684  2988.2   754.2 2987.01   874.6 2985.86   914.8 2984.76
   954.9 2984.91  1105.5 2983.92  1109.22983.927  1125.6 2984.12  1144.22985.301
  1195.8 2988.65    1246 2991.34    1256 2992.28  1286.1 2995.74  1326.3 3000.74
  1356.4 3004.76  1406.6 3012.25  1436.7  3017.6  1456.8  3021.5  1476.8 3025.66
#Mann= 3 , 0 , 0
       0      .1       0  1109.2    .045       0  1144.2      .1       0
Bank Sta=1109.2,1144.2
XS Rating Curve= 0 ,0
Exp/Cntr=0.3,0.1

Type RM Length L Ch R = 1 ,22019.9 ,346.1,346.1,345.1
XS GIS Cut Line= 2
     2110631.942       429873.86     2112033.004      430101.119
#Sta/Elev= 30
       0 3032.03    20.1 3028.27    50.3 3023.26    70.5 3020.49   100.7 3017.74
   140.9  3012.4   261.7  3000.1   291.9 2997.41   322.1 2993.51   342.3 2991.55
   372.5  2989.6   392.6 2988.78     453 2988.04   563.7 2984.11   583.9 2983.89
   704.6 2983.89   739.82984.384   774.82984.473   805.3  2983.9   946.2  2983.9
  1026.8 2984.63    1067 2985.47  1127.4  2989.2  1177.8 2994.06    1208 2997.35
  1258.3 3003.63  1278.4 3006.65  1308.6 3012.28    1359 3023.86  1419.4 3036.37
#Mann= 3 , 0 , 0
       0      .1       0   739.8    .045       0   774.8      .1       0
Bank Sta=739.8,774.8
XS Rating Curve= 0 ,0
Exp/Cntr=0.3,0.1

Type RM Length L Ch R = 1 ,21673.8 ,565.8,568.5,571.2
XS GIS Cut Line= 2
     2110774.468      430268.451     2112119.053      430370.299
#Sta/Elev= 30
       0 3019.57    40.2 3014.53   120.8 3005.82   191.2 2997.12   221.4 2993.84
   261.6 2990.31   301.9 2987.81   352.2 2985.61   412.6  2984.9   442.8    2984
   462.9 2983.89   477.1 2983.89   512.1 2983.89   553.5  2983.9   603.8 2984.82
   774.8 2985.18     805 2985.83   875.5 2989.14   895.6 2990.75   996.2 3002.93
  1016.4 3005.76  1096.9 3019.92    1117 3024.57  1177.4  3039.9  1237.8 3052.51
  1257.9 3057.17    1278 3063.22  1288.1 3066.83  1318.2    3079  1348.4 3090.33
#Mann= 3 , 0 , 0
       0      .1       0   477.1    .045       0   512.1      .1       0
Bank Sta=477.1,512.1
XS Rating Curve= 0 ,0
Exp/Cntr=0.3,0.1

Type RM Length L Ch R = 1 ,21105.2 ,450.4,455.4,453
XS GIS Cut Line= 2
     2110786.377      430743.381     2112127.879      431021.187
#Sta/Elev= 30
       0  3006.7    10.1 3004.61    20.2 3003.21   100.7 2995.38   120.9 2993.76
     141 2992.47   181.3 2990.48   211.5 2989.55   241.8    2989     272 2988.93
   362.6 2989.38     413 2988.93   443.2 2988.27   453.3 2987.88   503.7  2985.1
   526.72984.042     544 2983.89   561.72983.897   584.2 2984.18   614.5 2984.98
   765.6 2990.05   815.9 2991.56   856.2 2992.57   886.4 2993.09   936.8 2993.54
  1027.5 2994.72  1148.4 2996.71    1239 2998.97  1339.8    3001    1370 3001.74
#Mann= 3 , 0 , 0
       0      .1       0   526.7    .045       0   561.7      .1       0
Bank Sta=526.7,561.7
XS Rating Curve= 0 ,0
Exp/Cntr=0.3,0.1

Type RM Length L Ch R = 1 ,20649.8 ,438.5,439,439.5
XS GIS Cut Line= 2
        2110615.      430862.984     2111617.685      431294.254
#Sta/Elev= 30
       0 3017.32      10 3014.56      20 3012.16      30 3010.08    40.1 3008.35
    50.1 3007.26    80.1 3005.27   220.3 2995.42   250.3 2993.56   260.4 2993.07
   280.4 2992.48   340.5 2992.52   420.6 2991.16   470.6 2989.88   580.8 2986.53
   650.9 2984.94     731 2983.95   774.22983.951   791.1  2983.9   801.1 2983.96
   809.22984.397   811.1  2984.5   831.1 2987.14   861.2 2990.63   961.3 3001.72
   991.4 3004.84  1001.4 3005.63  1011.4 3006.09  1051.4 3007.12  1091.5 3007.72
#Mann= 3 , 0 , 0
       0      .1       0   774.2    .045       0   809.2      .1       0
Bank Sta=774.2,809.2
XS Rating Curve= 0 ,0
Exp/Cntr=0.3,0.1

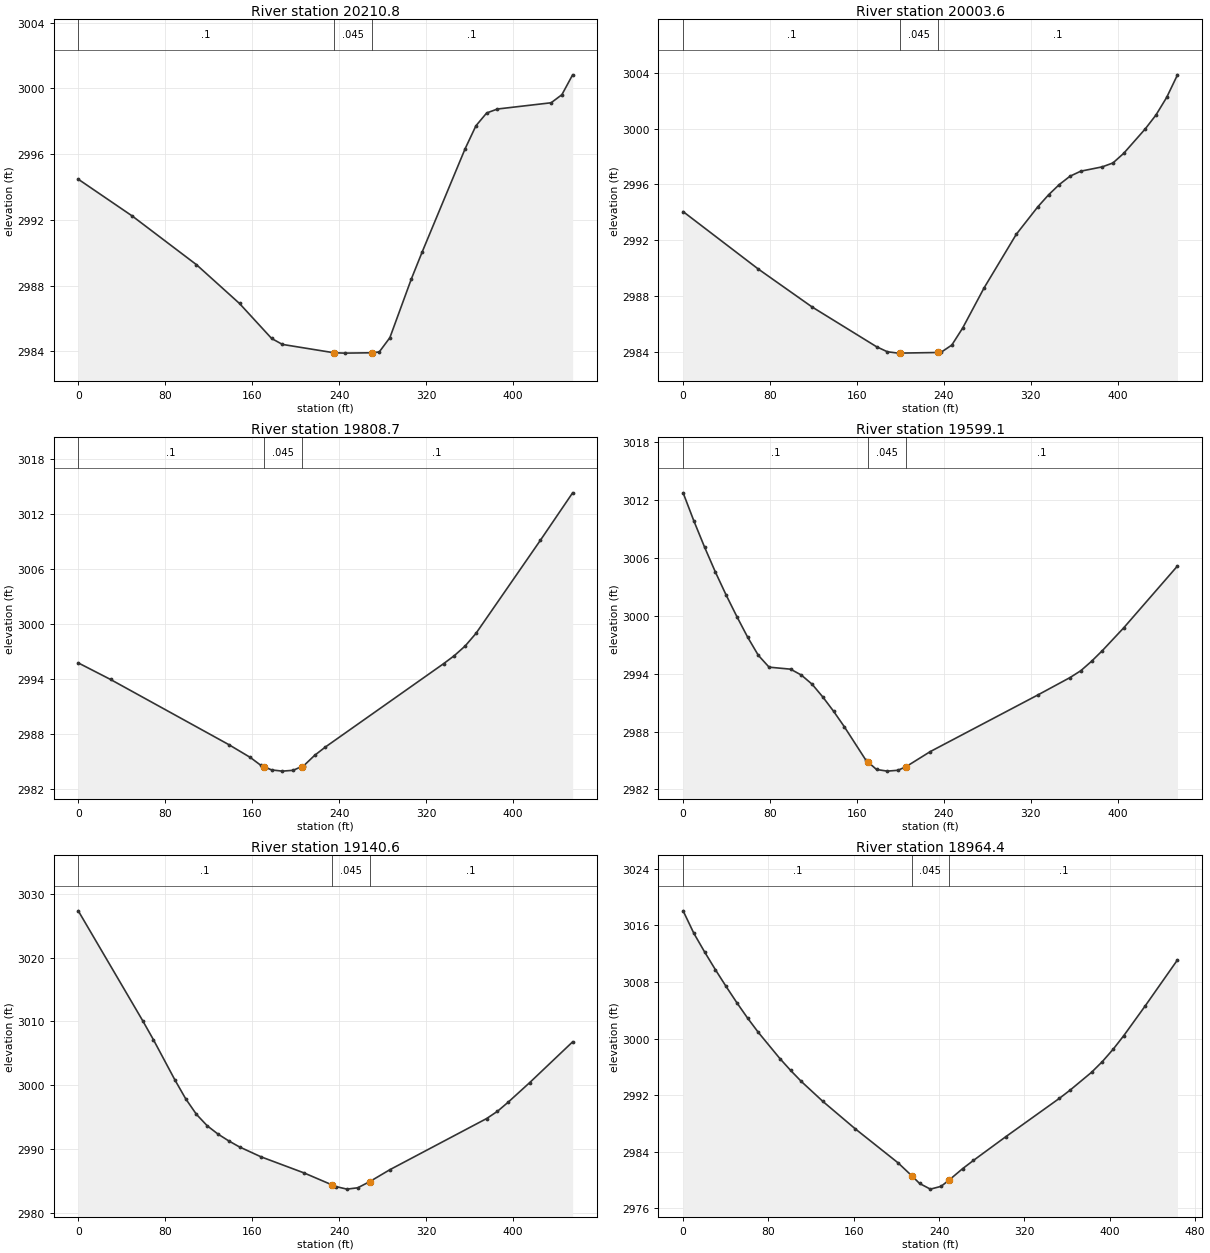
Type RM Length L Ch R = 1 ,20210.8 ,207.3,207.3,207.3
XS GIS Cut Line= 2
     2110842.316      431370.661     2111259.413      431552.472
#Sta/Elev= 20
       0 2994.47    49.5 2992.24   108.8 2989.27   148.4 2986.91     178 2984.78
   187.9 2984.42   235.22983.913   245.2 2983.89   270.22983.912     277 2983.96
   286.8 2984.83   306.6 2988.41   316.5 2990.04   356.1 2996.33     366 2997.72
   375.9  2998.5   385.8 2998.74   435.2 2999.12   445.1 2999.61     455 3000.82
#Mann= 3 , 0 , 0
       0      .1       0   235.2    .045       0   270.2      .1       0
Bank Sta=235.2,270.2
XS Rating Curve= 0 ,0
Exp/Cntr=0.3,0.1

Type RM Length L Ch R = 1 ,20003.6 ,190.5,194.8,199.1
XS GIS Cut Line= 3
     2110794.765      431573.067     2111003.314      431663.973
     2111211.862      431754.878
#Sta/Elev= 25
       0 2994.05    69.2 2989.93   118.7 2987.21     178 2984.36   187.9    2984
   197.8  2983.9   199.62983.902   234.62983.946   237.4 2983.96   247.3 2984.48
   257.2 2985.69     277 2988.58   306.6 2992.42   326.4 2994.39   336.3 2995.25
   346.2 2995.99   356.1 2996.59     366 2996.95   385.8 2997.26   395.6 2997.54
   405.5 2998.23   425.3 2999.98   435.2 3000.98   445.1 3002.25     455 3003.86
#Mann= 3 , 0 , 0
       0      .1       0   199.6    .045       0   234.6      .1       0
Bank Sta=199.6,234.6
XS Rating Curve= 0 ,0
Exp/Cntr=0.3,0.1

Type RM Length L Ch R = 1 ,19808.7 ,206.2,209.6,213.1
XS GIS Cut Line= 2
     2110735.514      431719.031     2111111.281      431975.593
#Sta/Elev= 19
       0 2995.73    29.7 2993.92   138.5  2986.8   158.3  2985.4   168.2 2984.52
   170.52984.405     178 2984.03   187.9  2983.9   197.8 2983.99   205.52984.395
   207.7 2984.51   217.6 2985.63   227.5 2986.54   336.3 2995.65   346.2 2996.53
   356.1 2997.58     366 2998.95   425.3 3009.13     455 3014.32
#Mann= 3 , 0 , 0
       0      .1       0   170.5    .045       0   205.5      .1       0
Bank Sta=170.5,205.5
XS Rating Curve= 0 ,0
Exp/Cntr=0.3,0.1

Type RM Length L Ch R = 1 ,19599.1 ,466.1,458.5,450.8
XS GIS Cut Line= 2
     2110616.455      431855.069     2110949.021      432165.592
#Sta/Elev= 29
       0 3012.77     9.9 3009.85    19.8 3007.12    29.7 3004.55    39.6 3002.16
    49.5 2999.92    59.4 2997.79    69.2 2995.91    79.1 2994.68    98.9 2994.47
   108.8 2993.86   118.7 2992.91   128.6 2991.58   138.5  2990.1   148.4 2988.49
   168.2 2985.03   170.32984.822     178 2984.06   187.9 2983.89   197.8 2983.98
   205.32984.359   227.5 2985.92   326.4 2991.79   356.1  2993.6     366 2994.31
   375.9 2995.29   385.8 2996.39   405.5 2998.76     455 3005.18
#Mann= 3 , 0 , 0
       0      .1       0   170.3    .045       0   205.3      .1       0
Bank Sta=170.3,205.3
XS Rating Curve= 0 ,0
Exp/Cntr=0.3,0.1

Type RM Length L Ch R = 1 ,19140.6 ,175.2,176.2,177.3
XS GIS Cut Line= 2
     2110296.597      432278.066     2110713.694      432459.877
#Sta/Elev= 23
       0 3027.34    59.4 3010.07    69.2 3007.11      89 3000.79    98.9 2997.84
   108.8  2995.4   118.7 2993.61   128.6 2992.31   138.5 2991.24   148.4 2990.29
   168.2 2988.74   207.7 2986.22   233.12984.368   237.4 2984.06   247.3 2983.67
   257.2 2983.88   268.12984.834   286.8 2986.72   375.9 2994.75   385.8 2995.88
   395.6  2997.3   415.4 3000.37     455 3006.78
#Mann= 3 , 0 , 0
       0      .1       0   233.1    .045       0   268.1      .1       0
Bank Sta=233.1,268.1
XS Rating Curve= 0 ,0
Exp/Cntr=0.3,0.1

Type RM Length L Ch R = 1 ,18964.4 ,460.5,465.7,470.9
XS GIS Cut Line= 2
     2110250.922      432437.542      2110666.68      432642.515
#Sta/Elev= 30
       0 3018.07    10.1 3014.88    20.2 3012.24    30.2 3009.76    40.3 3007.37
    50.4 3005.07    60.5 3002.89    70.5 3000.88    90.7 2997.18   100.8  2995.5
   110.8 2993.94     131 2991.12   161.2 2987.26   201.5 2982.43   214.32980.609
   221.7 2979.51   231.8 2978.71   241.8  2979.1   249.32979.984     262  2981.6
   272.1 2982.76   302.3  2986.1   352.7 2991.54   362.8 2992.71   382.9 2995.23
     393 2996.74   403.1 2998.48   413.2 3000.43   433.3 3004.64   463.5 3011.13
#Mann= 3 , 0 , 0
       0      .1       0   214.3    .045       0   249.3      .1       0
Bank Sta=214.3,249.3
XS Rating Curve= 0 ,0
Exp/Cntr=0.3,0.1