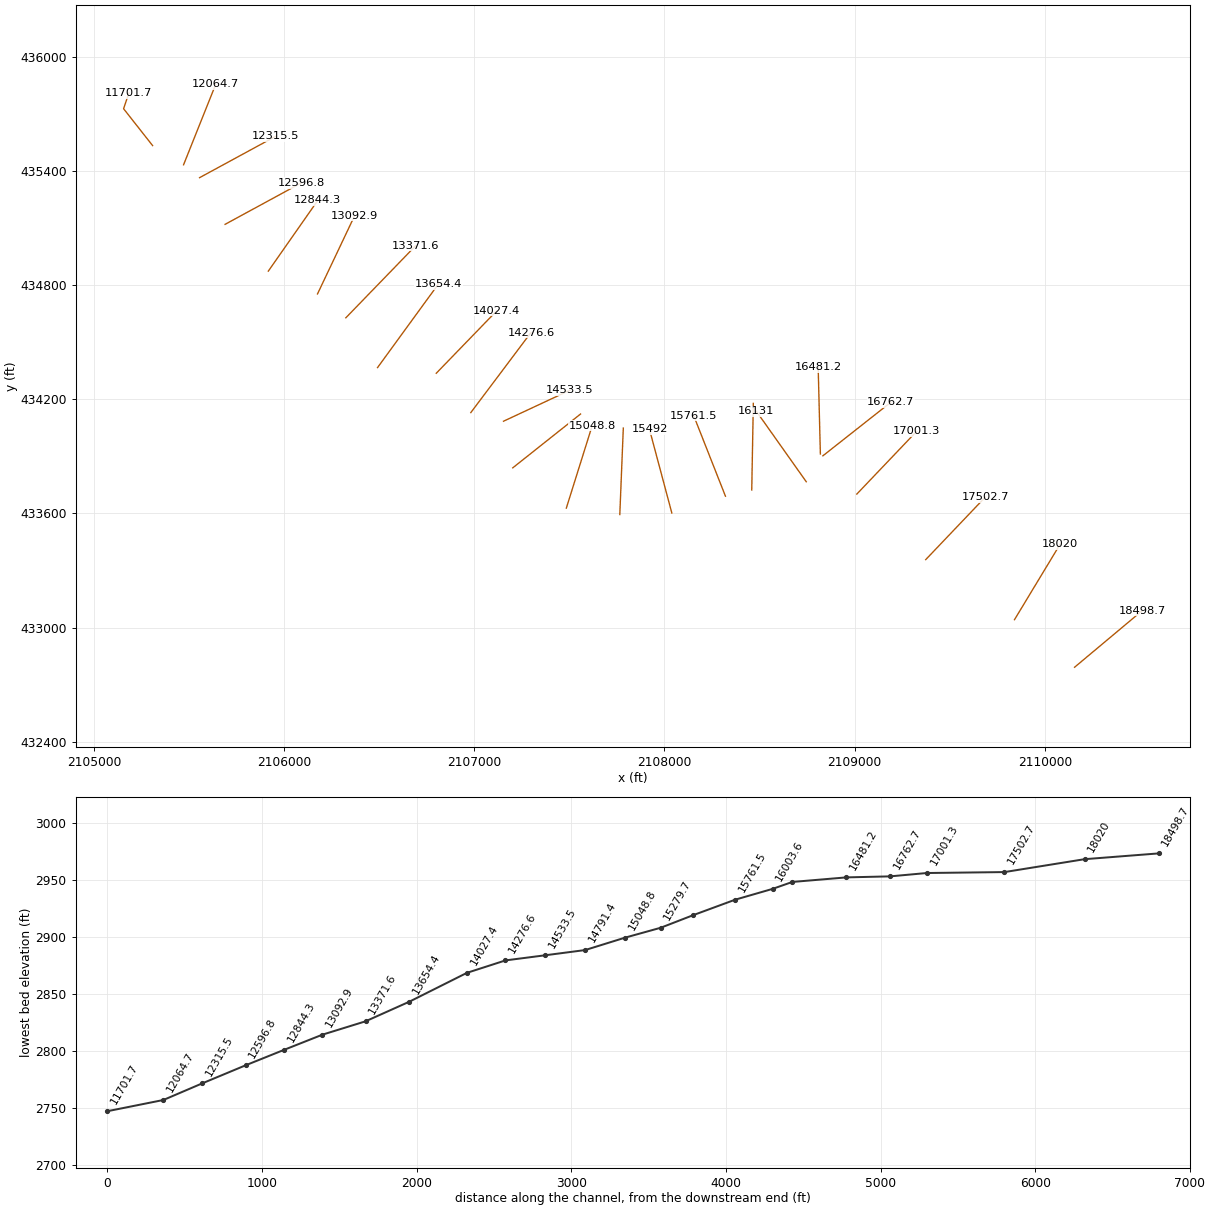
HEC-RAS study LitLaurCk.prj: LitLaurCk

--- LitLaurCk.g01 (geometry) --- (continued)

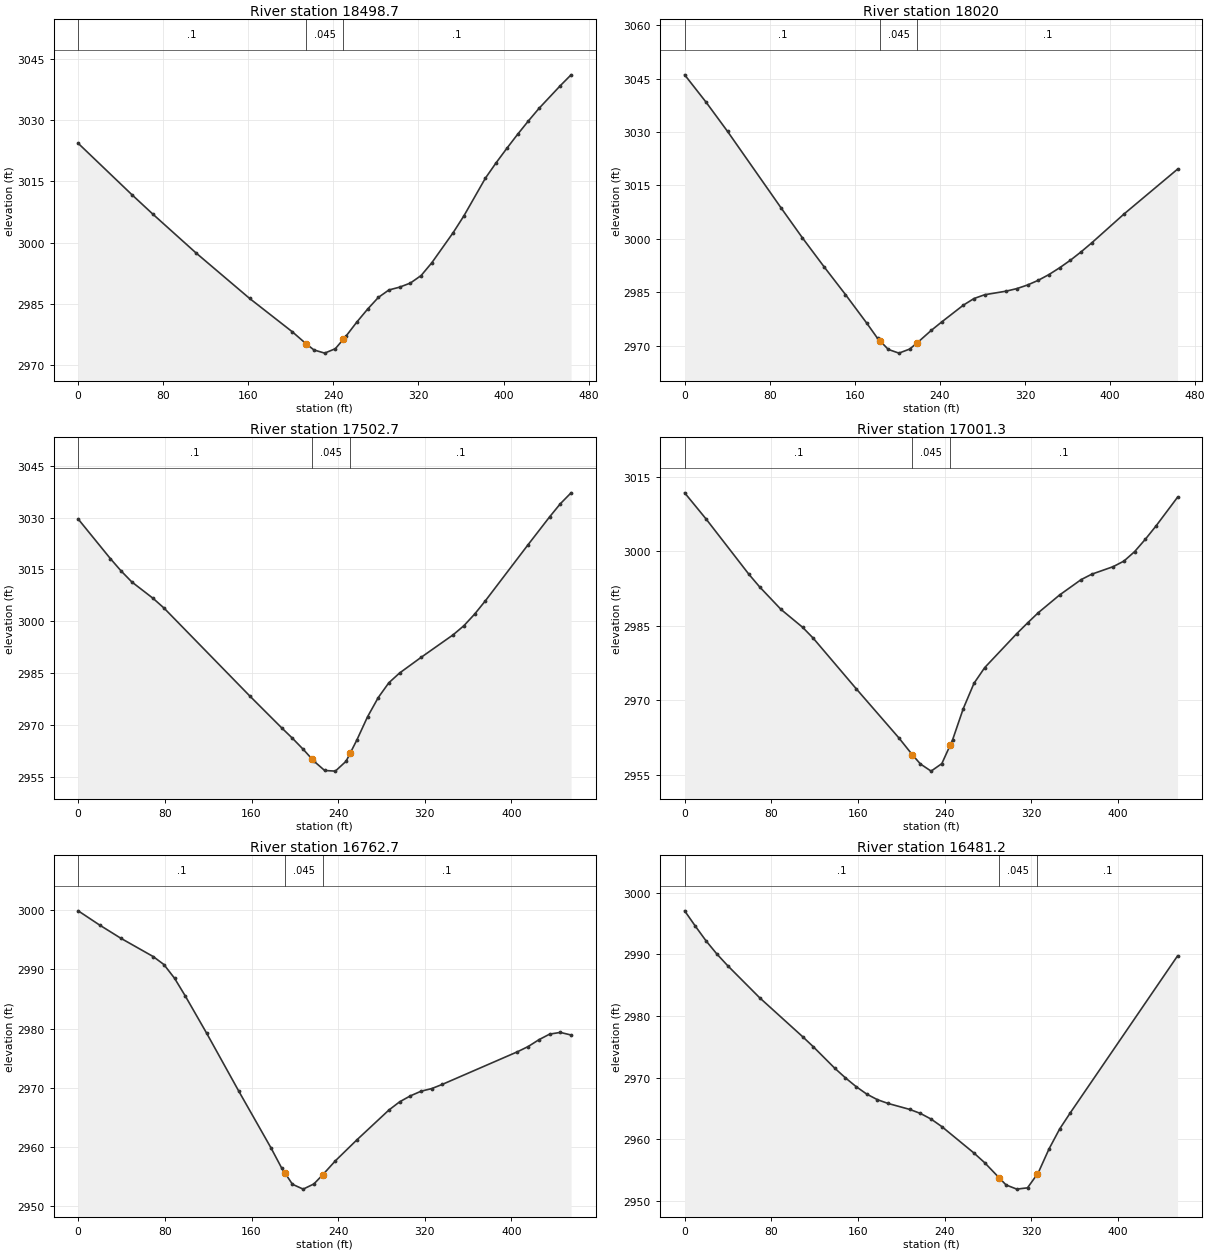
Type RM Length L Ch R = 1 ,18498.7 ,471.2,478.7,486.2
XS GIS Cut Line= 2
     2110156.305      432791.357     2110511.821      433088.808
#Sta/Elev= 30
       0 3024.27    50.4 3011.73    70.5 3006.88   110.8 2997.46   161.2 2986.33
   201.5 2978.14   214.32975.239   221.7 2973.73   231.8 2972.95   241.8 2974.03
   249.32976.325   251.9 2977.12     262 2980.54   272.1 2983.69   282.2 2986.56
   292.2  2988.4   302.3 2989.09   312.4 2990.09   322.5 2991.93   332.5 2995.04
   352.7 3002.45   362.8 3006.56   382.9 3015.73     393  3019.5   403.1 3023.04
   413.2 3026.46   423.2 3029.69   433.3  3032.8   453.5  3038.4   463.5 3041.02
#Mann= 3 , 0 , 0
       0      .1       0   214.3    .045       0   249.3      .1       0
Bank Sta=214.3,249.3
XS Rating Curve= 0 ,0
Exp/Cntr=0.3,0.1

Type RM Length L Ch R = 1 ,18020   ,522.2,517.3,512.4
XS GIS Cut Line= 2
     2109840.336      433041.388     2110080.187       433438.05
#Sta/Elev= 30
       0 3046.11    20.2  3038.4    40.3 3030.22    90.7 3008.69   110.8 3000.26
     131 2992.19   151.2 2984.35   171.3 2976.28   181.4 2972.03   183.92971.258
   191.5 2968.91   201.5 2967.87   211.6 2969.01   218.92970.817   231.8 2974.24
   241.8 2976.65     262 2981.34   272.1 2983.22   282.2 2984.29   302.3 2985.29
   312.4 2986.01   322.5 2987.03   332.5 2988.34   342.6 2989.96   352.7 2991.88
   362.8    2994   372.8 2996.34   382.9 2998.89   413.2 3006.99   463.5 3019.59
#Mann= 3 , 0 , 0
       0      .1       0   183.9    .045       0   218.9      .1       0
Bank Sta=183.9,218.9
XS Rating Curve= 0 ,0
Exp/Cntr=0.3,0.1

Type RM Length L Ch R = 1 ,17502.7 ,501.1,501.4,520.6
XS GIS Cut Line= 2
     2109373.556      433357.123     2109687.482      433686.479
#Sta/Elev= 30
       0 3029.59    29.7 3018.13    39.6 3014.56    49.5 3011.37    69.2  3006.6
    79.1 3003.84   158.3 2978.37   187.9 2969.09   197.8 2966.09   207.7  2962.9
   216.1 2959.99   217.6 2959.47   227.5 2956.76   237.4 2956.57   247.3 2959.43
   251.12961.779   257.2 2965.55   267.1  2972.3     277 2977.88   286.8 2982.17
   296.7 2984.99   316.5 2989.51   346.2 2996.07   356.1  2998.7     366 3002.06
   375.9 3005.91   415.4 3022.19   435.2 3030.22   445.1 3034.02     455 3037.18
#Mann= 3 , 0 , 0
       0      .1       0   216.1    .045       0   251.1      .1       0
Bank Sta=216.1,251.1
XS Rating Curve= 0 ,0
Exp/Cntr=0.3,0.1

Type RM Length L Ch R = 1 ,17001.3 ,241.9,238.6,235.5
XS GIS Cut Line= 3
     2109011.626      433702.097     2109168.589      433866.775
     2109325.552      434031.453
#Sta/Elev= 30
       0 3011.77    19.8  3006.5    59.4 2995.35    69.2 2992.84      89 2988.29
   108.8 2984.72   118.7 2982.51   158.3 2972.35   197.8 2962.43     2102959.096
   217.6  2957.2   227.5 2955.75   237.4 2957.26     2452960.914   247.3 2962.02
   257.2 2968.33   267.1 2973.43     277 2976.59   306.6 2983.43   316.5 2985.57
   326.4 2987.63   346.2 2991.22     366  2994.3   375.9  2995.4   395.6 2996.91
   405.5 2998.03   415.4 2999.94   425.3 3002.43   435.2 3005.12     455 3010.88
#Mann= 3 , 0 , 0
       0      .1       0     210    .045       0     245      .1       0
Bank Sta=210,245
XS Rating Curve= 0 ,0
Exp/Cntr=0.3,0.1

Type RM Length L Ch R = 1 ,16762.7 ,260.3,281.5,302.7
XS GIS Cut Line= 2
     2108833.153      433903.272     2109190.556      434184.854
#Sta/Elev= 30
       0 2999.93    19.8 2997.52    39.6 2995.26    69.2 2992.19    79.1 2990.84
      89  2988.5    98.9  2985.5   118.7 2979.17   148.4 2969.34     178 2959.78
   187.9 2956.35   190.72955.578   197.8 2953.62   207.7  2952.8   217.6 2953.68
   225.72955.218   237.4 2957.59   257.2 2961.13   286.8 2966.19   296.7 2967.58
   306.6 2968.59   316.5 2969.38   326.4 2969.83   336.3 2970.55   405.5 2976.06
   415.4 2976.95   425.3  2978.1   435.2 2979.05   445.1 2979.34     455  2978.9
#Mann= 3 , 0 , 0
       0      .1       0   190.7    .045       0   225.7      .1       0
Bank Sta=190.7,225.7
XS Rating Curve= 0 ,0
Exp/Cntr=0.3,0.1

Type RM Length L Ch R = 1 ,16481.2 ,336.1,350.2,365.3
XS GIS Cut Line= 2
      2108819.77       433912.69     2108808.202      434367.543
#Sta/Elev= 30
       0 2997.05     9.9 2994.56    19.8 2992.17    29.7 2990.06    39.6 2988.18
    69.2 2982.96   108.8 2976.66   118.7 2975.02   138.5 2971.54   148.4 2969.97
   158.3 2968.54   168.2 2967.32     178 2966.42   187.9 2965.81   207.7 2964.85
   217.6  2964.2   227.5 2963.28   237.4 2962.06   267.1 2957.77     277  2956.2
   290.62953.709   296.7  2952.6   306.6 2951.92   316.5 2952.13   325.62954.364
   326.4 2954.56   336.3 2958.42   346.2 2961.68   356.1 2964.32     455 2989.74
#Mann= 3 , 0 , 0
       0      .1       0   290.6    .045       0   325.6      .1       0
Bank Sta=290.6,325.6
XS Rating Curve= 0 ,0
Exp/Cntr=0.3,0.1

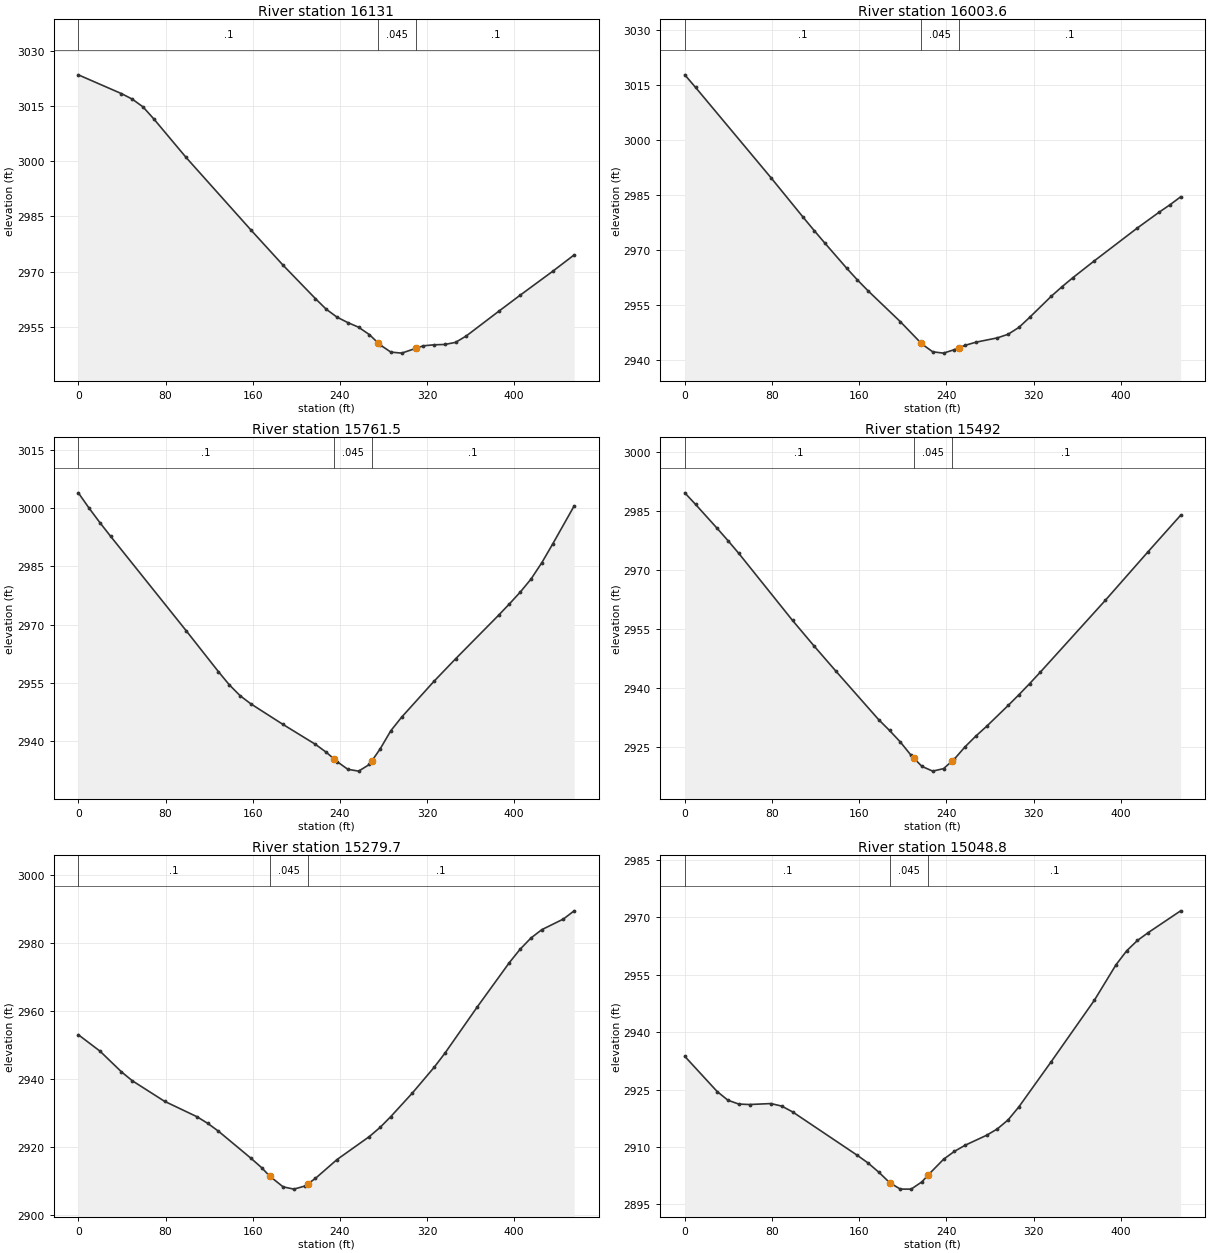
Type RM Length L Ch R = 1 ,16131   ,141.9,127.4,112.9
XS GIS Cut Line= 2
     2108745.374      433766.971     2108482.472      434138.331
#Sta/Elev= 28
       0 3023.42    39.6 3018.32    49.5 3016.83    59.4 3014.71    69.2 3011.48
    98.9    3001   158.3 2981.35   187.9 2971.76   217.6 2962.69   227.5 2959.82
   237.4 2957.67   247.3  2956.2   257.2 2954.94   267.1 2952.93   275.22950.647
     277 2950.14   286.8 2948.19   296.7 2947.91   310.2 2949.26   316.5 2949.89
   326.4 2950.17   336.3 2950.26   346.2 2950.83   356.1 2952.59   385.8 2959.27
   405.5 2963.64   435.2 2970.09     455 2974.56
#Mann= 3 , 0 , 0
       0      .1       0   275.2    .045       0   310.2      .1       0
Bank Sta=275.2,310.2
XS Rating Curve= 0 ,0
Exp/Cntr=0.3,0.1

Type RM Length L Ch R = 1 ,16003.6 ,233.2,242.2,251.1
XS GIS Cut Line= 2
     2108458.911      433723.726     2108467.218       434178.65
#Sta/Elev= 30
       0 3017.78     9.9 3014.34    79.1  2989.7   108.8 2978.85   118.7  2975.3
   128.6 2971.84   148.4 2965.07   158.3 2961.84   168.2 2958.84   197.8 2950.42
   216.6 2944.64   217.6 2944.33   227.5  2942.2   237.4 2941.84   247.3 2942.78
   251.62943.292   257.2 2943.96   267.1 2944.82   286.8    2946   296.7 2946.99
   306.6 2948.86   316.5 2951.61   336.3 2957.36   346.2 2959.97   356.1 2962.42
   375.9 2967.04   415.4 2976.01   435.2 2980.28   445.1 2982.29     455 2984.49
#Mann= 3 , 0 , 0
       0      .1       0   216.6    .045       0   251.6      .1       0
Bank Sta=216.6,251.6
XS Rating Curve= 0 ,0
Exp/Cntr=0.3,0.1

Type RM Length L Ch R = 1 ,15761.5 ,272.1,269.5,266.9
XS GIS Cut Line= 2
      2108320.66      433690.771     2108153.782      434114.064
#Sta/Elev= 30
       0 3003.95     9.9    3000    19.8 2996.28    29.7 2992.74    98.9  2968.5
   128.6 2957.93   138.5 2954.57   148.4 2951.77   158.3 2949.66   187.9 2944.35
   217.6 2939.24   227.5 2937.21   234.62935.482   237.4  2934.8   247.3 2932.82
   257.2 2932.35   267.1 2934.06   269.62935.075     277 2938.08   286.8 2942.76
   296.7 2946.24   326.4 2955.47   346.2 2961.25   385.8  2972.5   395.6 2975.38
   405.5  2978.4   415.4 2981.76   425.3 2985.97   435.2 2990.74     455 3000.58
#Mann= 3 , 0 , 0
       0      .1       0   234.6    .045       0   269.6      .1       0
Bank Sta=234.6,269.6
XS Rating Curve= 0 ,0
Exp/Cntr=0.3,0.1

Type RM Length L Ch R = 1 ,15492   ,219.1,212.3,205.4
XS GIS Cut Line= 3
     2108038.752      433602.311     2107980.016      433822.098
      2107921.28      434041.885
#Sta/Elev= 28
       0 2989.73     9.9 2986.78    29.7 2980.69    39.6 2977.57    49.5 2974.33
    98.9 2957.23   118.7 2950.71   138.5 2944.38     178 2931.95   187.9 2929.22
   197.8 2926.29   207.7 2922.88     2102922.229   217.6 2920.08   227.5 2918.87
   237.4  2919.5     2452921.358   247.3 2921.92   257.2 2925.07   267.1  2927.8
     277 2930.29   296.7 2935.58   306.6 2938.32   316.5 2941.17   326.4 2944.12
   385.8 2962.33   425.3 2974.79     455 2984.02
#Mann= 3 , 0 , 0
       0      .1       0     210    .045       0     245      .1       0
Bank Sta=210,245
XS Rating Curve= 0 ,0
Exp/Cntr=0.3,0.1

Type RM Length L Ch R = 1 ,15279.7 ,236.8,230.9,225
XS GIS Cut Line= 2
     2107765.183      433594.329     2107783.591      434048.957
#Sta/Elev= 30
       0    2953    19.8 2948.21    39.6 2942.11    49.5 2939.51    79.1 2933.48
   108.8 2928.96   118.7 2927.02   128.6  2924.7   158.3  2916.8   168.2 2914.01
   175.62911.533   187.9 2908.38   197.8 2907.71   207.7  2908.6   210.62909.265
   217.6 2910.87   237.4 2916.39   267.1 2923.14     277 2925.84   286.8 2929.01
   306.6 2935.93   326.4  2943.4   336.3 2947.54     366 2961.12   395.6 2974.19
   405.5 2978.12   415.4 2981.39   425.3 2983.82   445.1 2986.94     455 2989.35
#Mann= 3 , 0 , 0
       0      .1       0   175.6    .045       0   210.6      .1       0
Bank Sta=175.6,210.6
XS Rating Curve= 0 ,0
Exp/Cntr=0.3,0.1

Type RM Length L Ch R = 1 ,15048.8 ,271.1,257.4,243.7
XS GIS Cut Line= 2
     2107484.031       433628.18     2107620.224      434062.318
#Sta/Elev= 30
       0 2933.68    29.7 2924.49    39.6 2922.22    49.5 2921.22    59.4  2921.1
    79.1 2921.35      89 2920.68    98.9 2919.18   158.3 2907.84   168.2 2905.83
     178 2903.44   188.32900.623   197.8 2899.02   207.7 2899.01   217.6 2900.91
   223.32902.695   237.4 2906.79   247.3 2908.85   257.2 2910.46     277 2913.08
   286.8 2914.73   296.7 2917.09   306.6  2920.5   336.3 2932.31   375.9 2948.35
   395.6 2957.54   405.5 2961.24   415.4 2963.94   425.3 2965.99     455 2971.67
#Mann= 3 , 0 , 0
       0      .1       0   188.3    .045       0   223.3      .1       0
Bank Sta=188.3,223.3
XS Rating Curve= 0 ,0
Exp/Cntr=0.3,0.1

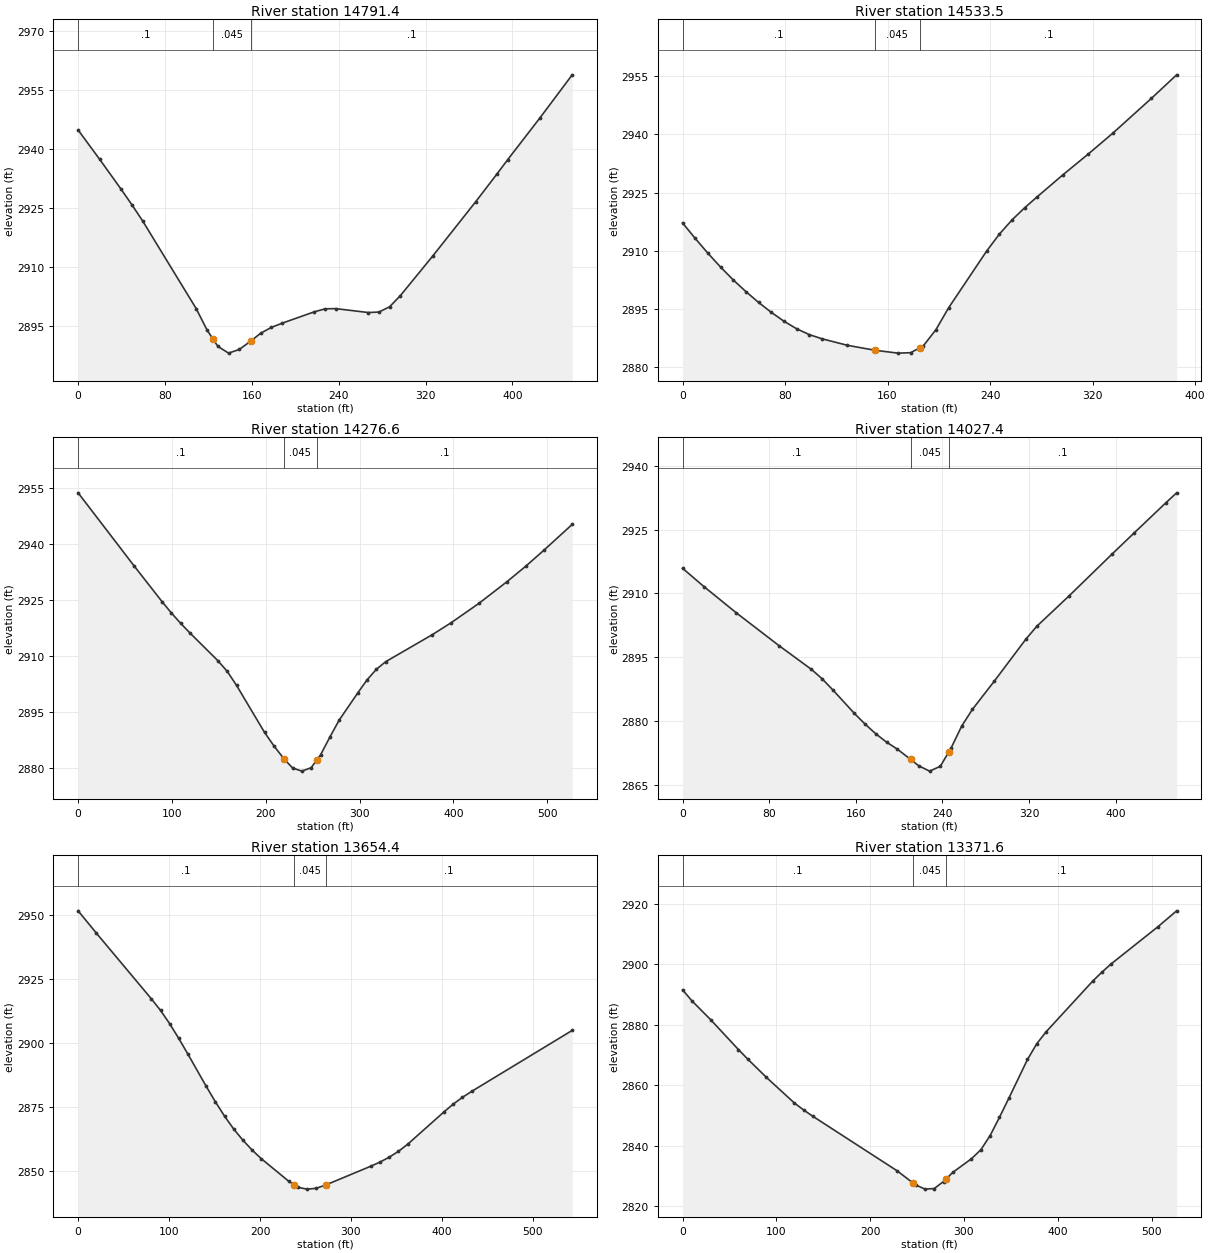
Type RM Length L Ch R = 1 ,14791.4 ,263.4,257.9,252.5
XS GIS Cut Line= 2
     2107202.443      433839.921     2107558.787      434122.841
#Sta/Elev= 28
       0 2944.91    19.8 2937.47    39.6 2929.84    49.5  2925.9    59.4 2921.79
   108.8 2899.44   118.7 2894.04     1242891.823   128.6  2889.9   138.5 2888.15
   148.4 2889.08     1592891.223   168.2 2893.23     178  2894.7   187.9 2895.77
   217.6 2898.67   227.5 2899.42   237.4 2899.47   267.1 2898.48     277  2898.6
   286.8 2899.93   296.7 2902.76   326.4  2912.8     366 2926.62   385.8 2933.76
   395.6 2937.37   425.3    2948     455 2958.95
#Mann= 3 , 0 , 0
       0      .1       0     124    .045       0     159      .1       0
Bank Sta=124,159
XS Rating Curve= 0 ,0
Exp/Cntr=0.3,0.1

Type RM Length L Ch R = 1 ,14533.5 ,245.2,256.9,285.9
XS GIS Cut Line= 2
     2107153.611      434084.961     2107503.067      434248.048
#Sta/Elev= 30
       0 2917.16     9.9 2913.16    19.8 2909.34    29.7 2905.76    39.6 2902.45
    49.4 2899.46    59.3 2896.67    69.2 2894.11    79.1 2891.82      89 2889.87
    98.9 2888.36   108.8 2887.28   128.6  2885.6   150.22884.316   168.1 2883.58
     178 2883.69   185.2 2884.97   187.9 2885.45   197.8 2889.66   207.6 2895.25
   237.3 2909.89   247.2 2914.25   257.1 2917.92     267 2921.07   276.9 2923.93
   296.6  2929.5   316.4 2934.86   336.2 2940.42   365.9 2949.28   385.6 2955.35
#Mann= 3 , 0 , 0
       0      .1       0   150.2    .045       0   185.2      .1       0
Bank Sta=150.2,185.2
XS Rating Curve= 0 ,0
Exp/Cntr=0.3,0.1

Type RM Length L Ch R = 1 ,14276.6 ,253.3,249.2,245.3
XS GIS Cut Line= 2
     2106981.781      434130.331     2107298.177      434551.353
#Sta/Elev= 30
       0 2953.75    59.6 2934.17    89.4 2924.58    99.4 2921.52   109.3 2918.74
   119.2 2916.15     149 2908.71     159 2905.83   168.9 2902.08   198.7 2889.48
   208.7 2885.86   219.42882.386   228.6 2879.93   238.5 2879.08   248.4    2880
   254.42882.058   258.4 2883.43   268.3 2888.18   278.2 2892.74   298.1 2900.06
     308 2903.57     318 2906.42   327.9 2908.45   377.6  2915.7   397.5 2918.87
   427.3  2924.1   457.1  2929.9     477 2934.02   496.8 2938.41   526.7 2945.28
#Mann= 3 , 0 , 0
       0      .1       0   219.4    .045       0   254.4      .1       0
Bank Sta=219.4,254.4
XS Rating Curve= 0 ,0
Exp/Cntr=0.3,0.1

Type RM Length L Ch R = 1 ,14027.4 ,372.2,373,360.5
XS GIS Cut Line= 2
      2106800.19      434337.235     2107117.498      434664.933
#Sta/Elev= 28
       0  2915.9    19.8 2911.58    49.6 2905.42    89.2 2897.67     119 2892.11
   128.9 2889.89   138.8 2887.27   158.7 2881.74   168.6 2879.22   178.5 2876.94
   188.4 2874.98   198.3 2873.35   210.6 2870.92   218.2  2869.4   228.1 2868.17
     238 2869.31   245.62872.588   247.9 2873.58   257.8  2878.8   267.7 2882.72
   287.6 2889.26   317.3 2899.32   327.2 2902.28     357 2909.43   396.6 2919.25
   416.5  2924.1   446.2  2931.3   456.2 2933.65
#Mann= 3 , 0 , 0
       0      .1       0   210.6    .045       0   245.6      .1       0
Bank Sta=210.6,245.6
XS Rating Curve= 0 ,0
Exp/Cntr=0.3,0.1

Type RM Length L Ch R = 1 ,13654.4 ,283.9,282.8,291
XS GIS Cut Line= 2
      2106491.21      434366.788     2106811.082      434805.916
#Sta/Elev= 30
       0 2951.76    20.1 2943.02    80.5 2917.33    90.6 2912.79   100.6 2907.61
   110.7  2901.8   120.7 2895.68   140.8 2883.09   150.9 2877.03     161  2871.4
     171 2866.38   181.1 2862.01   191.2 2858.17   201.2  2854.8   231.4 2845.96
   237.12844.605   241.5 2843.56   251.5 2842.82   261.6 2843.12   272.12844.414
   321.9  2851.8     332 2853.42   342.1 2855.32   352.1 2857.58   362.2 2860.34
   402.4 2873.09   412.5 2876.11   422.6 2878.76   432.6 2881.05   543.3 2904.95
#Mann= 3 , 0 , 0
       0      .1       0   237.1    .045       0   272.1      .1       0
Bank Sta=237.1,272.1
XS Rating Curve= 0 ,0
Exp/Cntr=0.3,0.1

Type RM Length L Ch R = 1 ,13371.6 ,273.2,278.7,285.8
XS GIS Cut Line= 2
     2106324.655      434628.705     2106691.036      435007.031
#Sta/Elev= 30
       0 2891.57     9.9 2887.94    29.8 2881.73    59.6 2871.79    69.6 2868.61
    89.4  2862.6   119.2 2854.12   129.2 2851.78   139.1 2849.68   228.6 2831.72
   245.8 2827.63   248.4 2827.05   258.4 2825.63   268.3 2825.83   278.2 2828.15
   280.82828.943   288.2  2831.2     308 2835.69     318 2838.66   327.9 2843.36
   337.8 2849.37   347.8 2855.68   367.7 2868.52   377.6 2873.73   387.5 2877.66
   437.2 2894.43   447.2 2897.45   457.1 2900.19   506.8 2912.44   526.7 2917.69
#Mann= 3 , 0 , 0
       0      .1       0   245.8    .045       0   280.8      .1       0
Bank Sta=245.8,280.8
XS Rating Curve= 0 ,0
Exp/Cntr=0.3,0.1

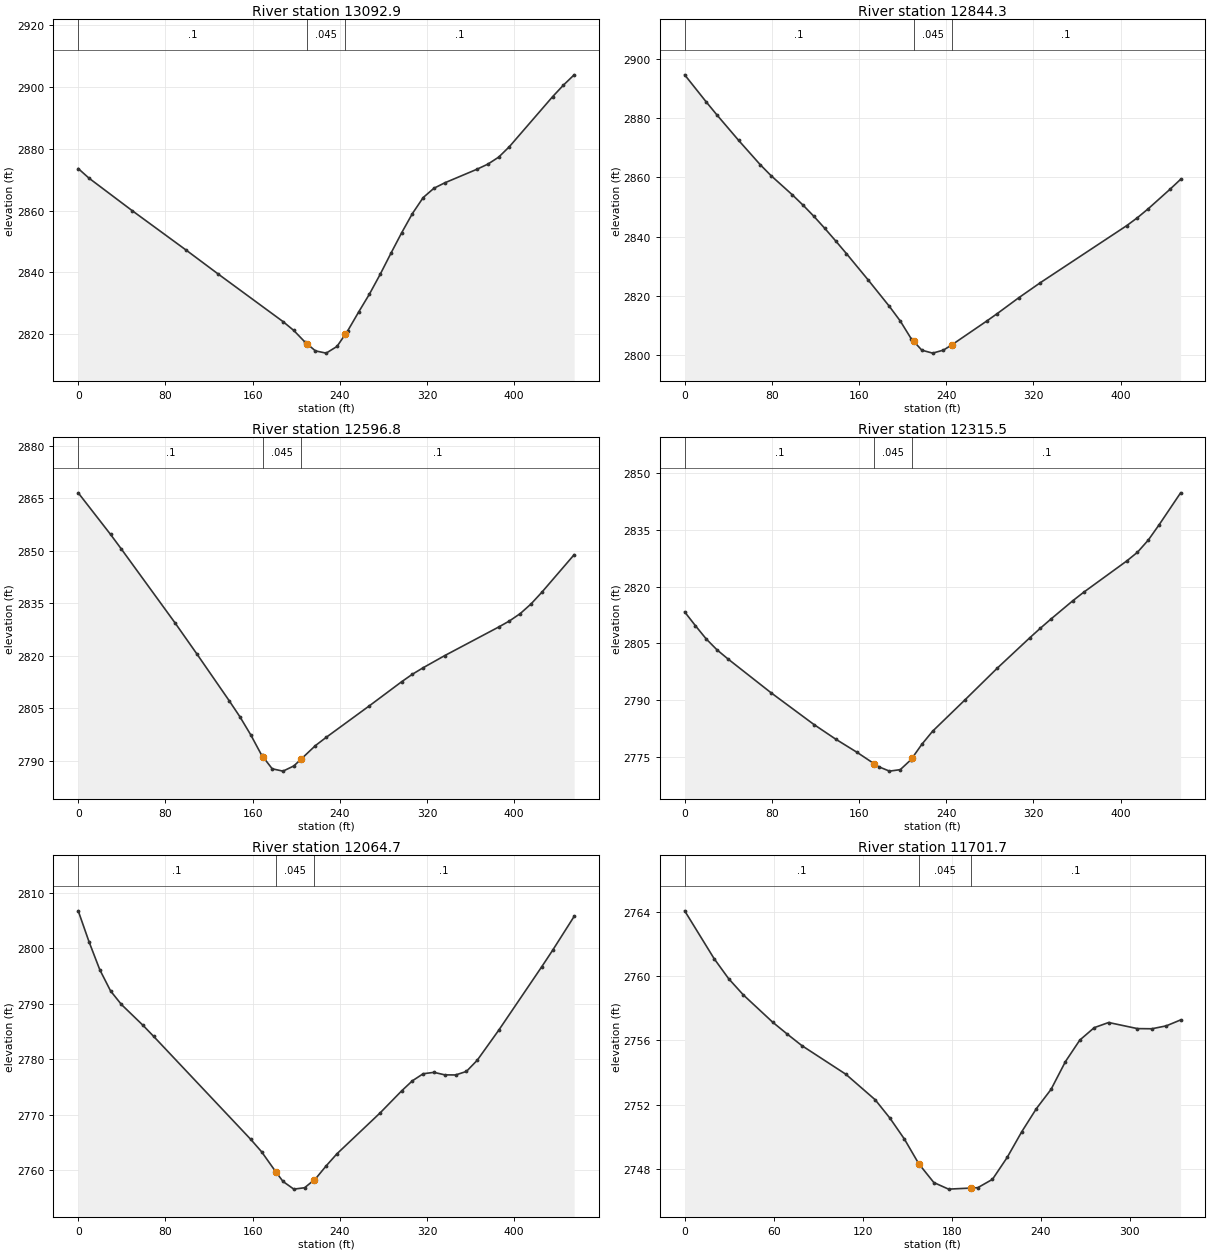
Type RM Length L Ch R = 1 ,13092.9 ,252.5,248.7,244.9
XS GIS Cut Line= 2
     2106175.712      434754.293     2106370.802      435165.347
#Sta/Elev= 30
       0  2873.6     9.9 2870.49    49.5 2859.99    98.9 2847.26   128.6 2839.45
   187.9 2824.12   197.8 2821.24   207.7 2817.62     210 2816.93   217.6 2814.65
   227.5 2813.92   237.4 2816.08     245 2819.98   247.3 2821.16   257.2 2827.16
   267.1 2832.96     277 2839.37   286.8 2846.14   296.7  2852.8   306.6 2859.04
   316.5 2864.22   326.4 2867.24   336.3 2868.98     366  2873.4   375.9 2875.04
   385.8  2877.3   395.6 2880.68   435.2 2896.82   445.1 2900.55     455  2903.9
#Mann= 3 , 0 , 0
       0      .1       0     210    .045       0     245      .1       0
Bank Sta=210,245
XS Rating Curve= 0 ,0
Exp/Cntr=0.3,0.1

Type RM Length L Ch R = 1 ,12844.3 ,257.9,247.5,237
XS GIS Cut Line= 2
     2105916.918      434874.027     2106177.696       435246.88
#Sta/Elev= 30
       0 2894.74    19.8 2885.56    29.7 2881.12    49.5 2872.56    69.2 2864.38
    79.1 2860.67    98.9 2854.09   108.8 2850.57   118.7  2846.8   128.6 2842.76
   138.5 2838.55   148.4 2834.24   168.2 2825.39   187.9 2816.34   197.8 2811.43
   207.7 2805.51     210 2804.59   217.6 2801.55   227.5 2800.56   237.4 2801.58
     245 2803.33     277 2811.39   286.8 2813.95   306.6 2819.33   326.4 2824.42
   405.5 2843.69   415.4  2846.4   425.3 2849.42   445.1 2855.96     455 2859.38
#Mann= 3 , 0 , 0
       0      .1       0     210    .045       0     245      .1       0
Bank Sta=210,245
XS Rating Curve= 0 ,0
Exp/Cntr=0.3,0.1

Type RM Length L Ch R = 1 ,12596.8 ,281,281.3,281.5
XS GIS Cut Line= 3
     2105689.759      435120.204     2105889.646      435228.839
     2106089.533      435337.474
#Sta/Elev= 27
       0 2866.59    29.7 2854.69    39.6 2850.52      89 2829.35   108.8 2820.58
   138.5 2807.19   148.4 2802.57   158.3 2797.42   168.2 2791.67   169.52791.146
     178 2787.72   187.9 2787.06   197.8 2788.54   204.52790.489   217.6 2794.35
   227.5 2796.71   267.1 2805.72   296.7  2812.6   306.6 2814.75   316.5 2816.61
   336.3 2820.08   385.8 2828.25   395.6 2829.97   405.5 2832.07   415.4 2834.82
   425.3 2838.16     455 2848.91
#Mann= 3 , 0 , 0
       0      .1       0   169.5    .045       0   204.5      .1       0
Bank Sta=169.5,204.5
XS Rating Curve= 0 ,0
Exp/Cntr=0.3,0.1

Type RM Length L Ch R = 1 ,12315.5 ,235.2,250.8,266.4
XS GIS Cut Line= 2
     2105555.612      435365.576     2105955.386      435582.845
#Sta/Elev= 29
       0 2813.28     9.9 2809.62    19.8 2806.12    29.7 2803.24    39.6 2800.87
    79.1 2791.93   118.7 2783.48   138.5 2779.64   158.3 2776.11   173.6 2773.17
     178 2772.33   187.9 2771.17   197.8 2771.56   207.7 2774.22   208.62774.588
   217.6 2778.27   227.5 2781.74   257.2 2790.03   286.8 2798.41   316.5 2806.41
   326.4 2808.99   336.3 2811.46   356.1 2816.24     366 2818.47   405.5 2826.74
   415.4 2829.06   425.3 2832.27   435.2  2836.3     455 2844.78
#Mann= 3 , 0 , 0
       0      .1       0   173.6    .045       0   208.6      .1       0
Bank Sta=173.6,208.6
XS Rating Curve= 0 ,0
Exp/Cntr=0.3,0.1

Type RM Length L Ch R = 1 ,12064.7 ,338.7,363,387.3
XS GIS Cut Line= 3
     2105471.443      435433.156     2105555.847      435644.419
     2105640.252      435855.682
#Sta/Elev= 30
       0 2806.73     9.9 2801.17    19.8 2796.12    29.7  2792.3    39.6 2789.87
    59.4 2786.12    69.2 2784.12   158.3 2765.57   168.2 2763.35   181.2 2759.75
   187.9 2757.99   197.8 2756.61   207.7 2756.86   216.22758.217   217.6 2758.44
   227.5  2760.8   237.4 2762.98     277 2770.34   296.7  2774.3   306.6 2776.12
   316.5 2777.39   326.4 2777.64   336.3 2777.19   346.2 2777.17   356.1  2777.8
     366  2779.8   385.8 2785.23   425.3 2796.67   435.2 2799.61     455 2805.73
#Mann= 3 , 0 , 0
       0      .1       0   181.2    .045       0   216.2      .1       0
Bank Sta=181.2,216.2
XS Rating Curve= 0 ,0
Exp/Cntr=0.3,0.1

Type RM Length L Ch R = 1 ,11701.7 ,115.3,124.9,135.5
XS GIS Cut Line= 3
     2105308.741      435534.113     2105155.998      435728.105
     2105184.154      435810.734
#Sta/Elev= 29
       0 2764.07    19.8  2761.1    29.6 2759.85    39.5 2758.84    59.3 2757.14
    69.1  2756.4      79 2755.68   108.6  2753.9   128.4 2752.31   138.3 2751.17
   148.1 2749.86   157.82748.322   167.9 2747.16   177.8 2746.75   192.82746.816
   197.5 2746.84   207.4 2747.36   217.3 2748.72   227.2 2750.33     237 2751.76
   246.9 2752.96   256.6 2754.69   266.3 2756.03     276  2756.8   285.7 2757.12
   305.1 2756.74   314.8 2756.73   324.5 2756.91   334.2 2757.28
#Mann= 3 , 0 , 0
       0      .1       0   157.8    .045       0   192.8      .1       0
Bank Sta=157.8,192.8
XS Rating Curve= 0 ,0
Exp/Cntr=0.3,0.1