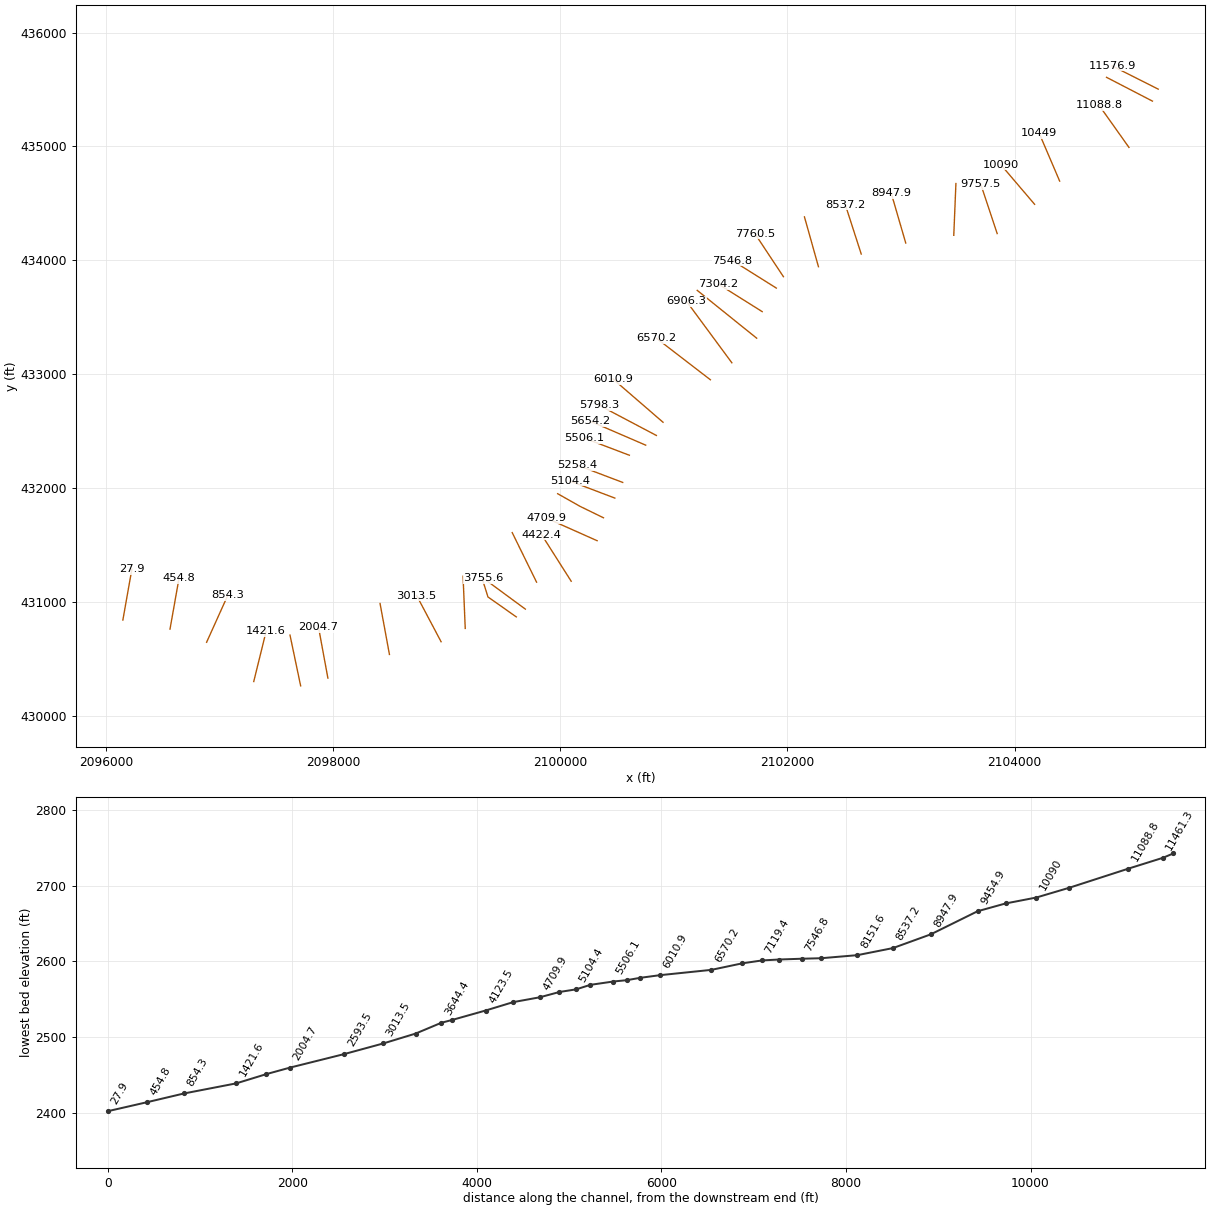
HEC-RAS study LitLaurCk.prj: LitLaurCk

--- LitLaurCk.g01 (geometry) --- (continued)

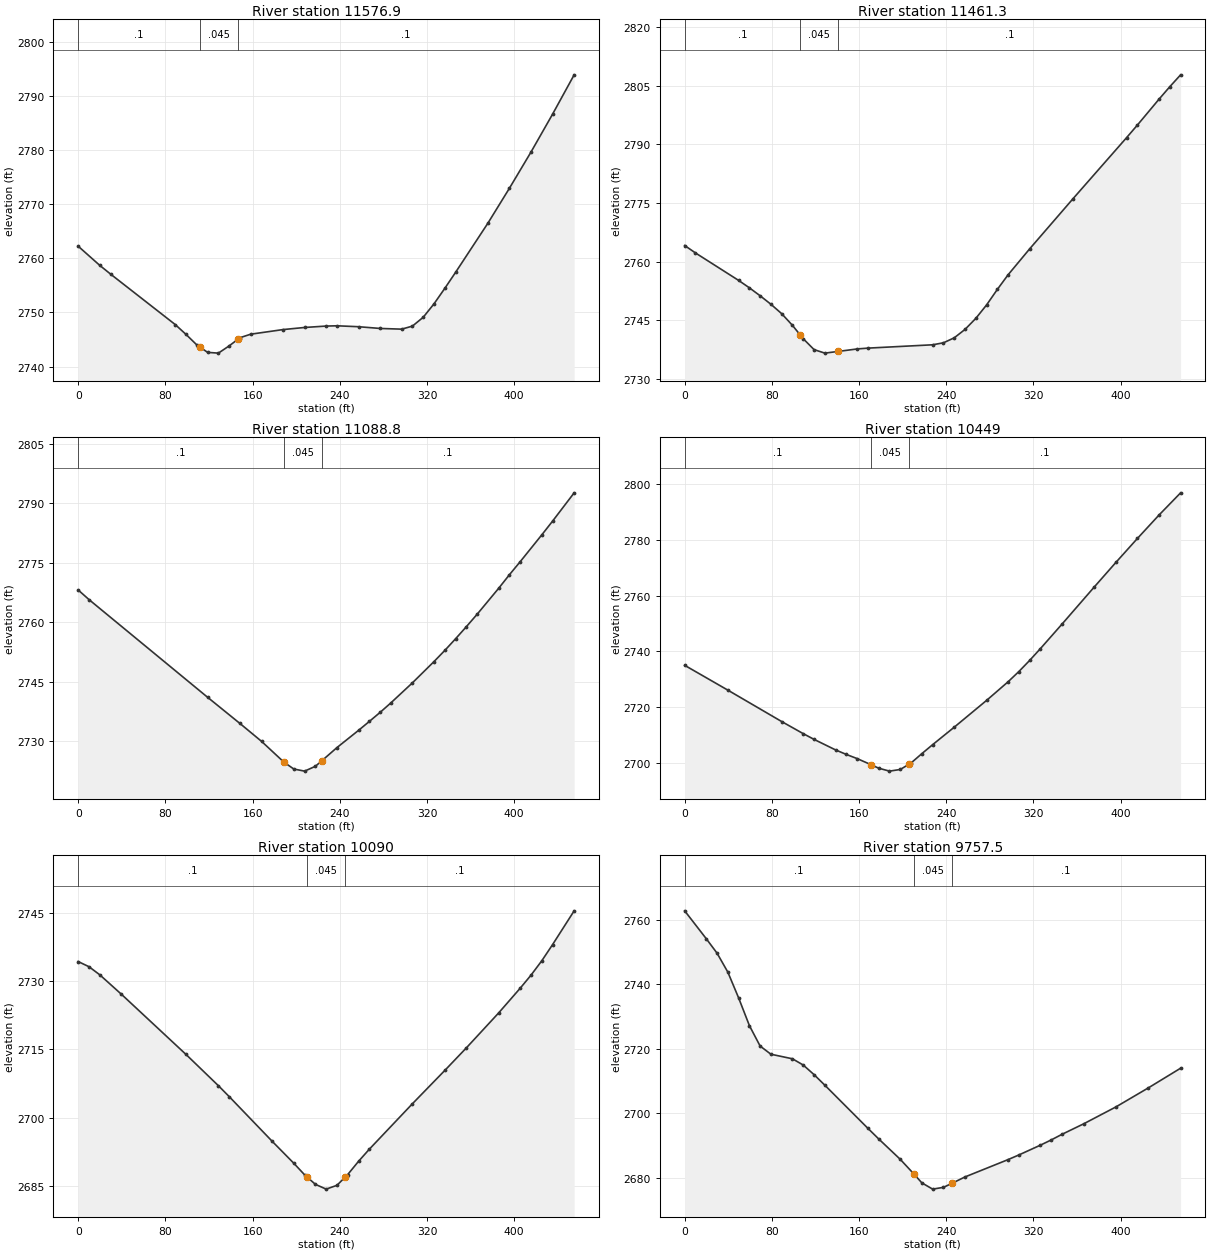
Type RM Length L Ch R = 1 ,11576.9 ,115.8,115.6,115.4
XS GIS Cut Line= 3
     2105263.528       435502.89     2105060.271      435605.081
     2104857.014      435707.271
#Sta/Elev= 30
       0 2762.23    19.8 2758.69    29.7 2757.08      89 2747.76    98.9 2745.94
   108.8    2744   111.6 2743.61   118.7 2742.62   128.6 2742.48   138.5 2743.82
   146.62745.055   148.4 2745.33   158.3 2745.98   187.9 2746.83   207.7 2747.22
   227.5 2747.48   237.4 2747.53   257.2 2747.36     277 2747.04   296.7 2746.91
   306.6 2747.47   316.5  2749.1   326.4 2751.58   336.3 2754.44   346.2  2757.4
   375.9  2766.5   395.6 2772.94   415.4 2779.63   435.2 2786.63     455  2793.9
#Mann= 3 , 0 , 0
       0      .1       0   111.6    .045       0   146.6      .1       0
Bank Sta=111.6,146.6
XS Rating Curve= 0 ,0
Exp/Cntr=0.3,0.1

Type RM Length L Ch R = 1 ,11461.3 ,383.4,372.5,361.5
XS GIS Cut Line= 2
      2105212.76      435397.775     2104808.523      435606.623
#Sta/Elev= 30
       0 2764.12     9.9 2762.22    49.5  2755.2    59.4  2753.3    69.2 2751.28
    79.1 2749.11      89  2746.7    98.9 2743.71     1062741.257   108.8 2740.29
   118.7 2737.52   128.6 2736.62     1412737.061   158.3 2737.69   168.2  2737.9
   227.5 2738.75   237.4 2739.26   247.3 2740.53   257.2 2742.68   267.1  2745.5
     277 2748.94   286.8 2752.88   296.7 2756.63   316.5 2763.26   356.1 2776.02
   405.5  2791.7   415.4 2794.91   435.2 2801.51   445.1  2804.7     455 2807.73
#Mann= 3 , 0 , 0
       0      .1       0     106    .045       0     141      .1       0
Bank Sta=106,141
XS Rating Curve= 0 ,0
Exp/Cntr=0.3,0.1

Type RM Length L Ch R = 1 ,11088.8 ,644.5,639.8,635.1
XS GIS Cut Line= 3
      2105005.83      434991.371     2104873.945      435176.742
      2104742.06      435362.113
#Sta/Elev= 27
       0 2768.15     9.9 2765.73   118.7 2741.06   148.4 2734.44   168.2 2729.93
   188.62724.706   197.8 2722.94   207.7 2722.41   217.6 2723.63   223.62725.048
   237.4 2728.36   257.2 2732.71   267.1 2734.96     277 2737.25   286.8 2739.63
   306.6  2744.7   326.4 2750.07   336.3 2752.88   346.2 2755.83   356.1 2758.88
     366 2762.03   385.8  2768.6   395.6    2772   405.5  2775.3   425.3 2782.07
   435.2 2785.54     455 2792.69
#Mann= 3 , 0 , 0
       0      .1       0   188.6    .045       0   223.6      .1       0
Bank Sta=188.6,223.6
XS Rating Curve= 0 ,0
Exp/Cntr=0.3,0.1

Type RM Length L Ch R = 1 ,10449   ,352.1,359,365.9
XS GIS Cut Line= 2
     2104395.825      434695.563     2104216.592      435113.774
#Sta/Elev= 28
       0 2735.05    39.6 2726.18      89 2714.95   108.8 2710.62   118.7 2708.58
   138.5  2704.8   148.4 2703.18   158.3  2701.7   170.72699.576     178 2698.28
   187.9 2697.23   197.8 2697.82   205.72699.671   207.7 2700.14   217.6 2703.48
   227.5 2706.69   247.3 2712.93     277 2722.52   296.7 2729.16   306.6 2732.82
   316.5  2736.8   326.4 2741.03   346.2 2749.78   375.9  2763.1   395.6 2771.82
   415.4 2780.41   435.2 2788.77     455  2796.7
#Mann= 3 , 0 , 0
       0      .1       0   170.7    .045       0   205.7      .1       0
Bank Sta=170.7,205.7
XS Rating Curve= 0 ,0
Exp/Cntr=0.3,0.1

Type RM Length L Ch R = 1 ,10090   ,341.4,332.5,323.6
XS GIS Cut Line= 2
     2104175.428      434491.789     2103879.742      434837.614
#Sta/Elev= 27
       0 2734.25     9.9 2733.12    19.8 2731.34    39.6 2727.08    98.9 2713.86
   128.6    2707   138.5 2704.61     178 2694.78   197.8 2689.97   207.7 2687.43
     2102686.945   217.6 2685.34   227.5 2684.29   237.4 2685.13     2452686.949
   247.3  2687.5   257.2  2690.4   267.1 2693.06   306.6 2703.03   336.3 2710.34
   356.1  2715.3   385.8 2722.99   405.5  2728.4   415.4 2731.26   425.3 2734.42
   435.2 2737.97     455 2745.39
#Mann= 3 , 0 , 0
       0      .1       0     210    .045       0     245      .1       0
Bank Sta=210,245
XS Rating Curve= 0 ,0
Exp/Cntr=0.3,0.1

Type RM Length L Ch R = 1 ,9757.5  ,310.9,302.5,294.2
XS GIS Cut Line= 2
     2103845.941      434234.758     2103701.998      434666.389
#Sta/Elev= 30
       0 2762.74    19.8  2754.1    29.7 2749.62    39.6 2743.74    49.5 2735.75
    59.4 2727.15    69.2 2720.84    79.1  2718.3    98.9 2716.88   108.8 2714.94
   118.7 2711.97   128.6  2708.7   168.2  2695.3     178 2692.05   197.8 2685.72
     2102681.286   217.6 2678.43   227.5 2676.49   237.4 2677.04     2452678.253
   257.2 2680.27   296.7 2685.64   306.6 2687.08   326.4 2690.12   336.3 2691.74
   346.2 2693.48     366 2696.72   395.6 2701.96   425.3 2707.85     455 2713.97
#Mann= 3 , 0 , 0
       0      .1       0     210    .045       0     245      .1       0
Bank Sta=210,245
XS Rating Curve= 0 ,0
Exp/Cntr=0.3,0.1

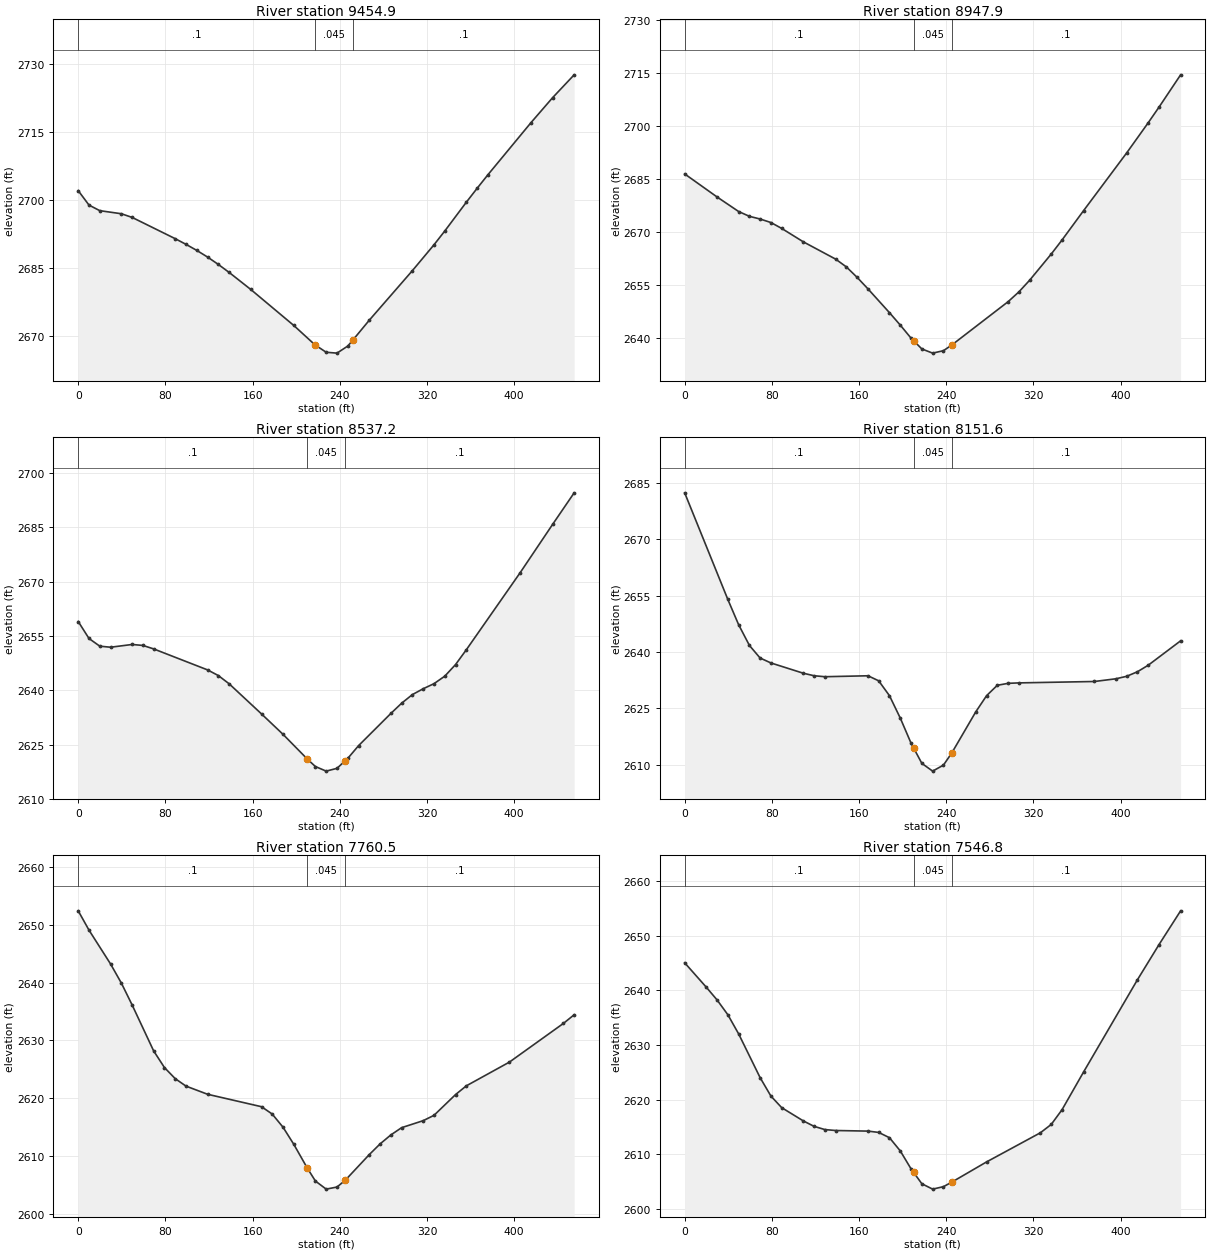
Type RM Length L Ch R = 1 ,9454.9  ,499.7,507.1,514.4
XS GIS Cut Line= 3
     2103463.858      434219.428      2103473.28      434446.732
     2103482.702      434674.037
#Sta/Elev= 28
       0 2702.11     9.9 2698.92    19.8 2697.69    39.6 2697.01    49.5  2696.2
      89 2691.51    98.9 2690.26   108.8 2688.92   118.7 2687.45   128.6 2685.82
   138.5 2684.06   158.3 2680.31   197.8 2672.36   217.1 2668.11   227.5 2666.45
   237.4 2666.26   247.3 2667.82   252.12669.177   267.1 2673.54   306.6 2684.46
   326.4 2690.16   336.3  2693.2   356.1 2699.56     366 2702.63   375.9 2705.62
   415.4 2717.11   435.2 2722.61     455 2727.66
#Mann= 3 , 0 , 0
       0      .1       0   217.1    .045       0   252.1      .1       0
Bank Sta=217.1,252.1
XS Rating Curve= 0 ,0
Exp/Cntr=0.3,0.1

Type RM Length L Ch R = 1 ,8947.9  ,410,410.7,411.3
XS GIS Cut Line= 2
     2103041.146      434151.478     2102913.677      434588.258
#Sta/Elev= 30
       0 2686.52    29.7    2680    49.5 2675.88    59.4 2674.52    69.2 2673.76
    79.1 2672.77      89  2671.1   108.8 2667.31   138.5 2662.41   148.4 2660.19
   158.3 2657.22   168.2 2653.98   187.9 2647.25   197.8 2643.74   207.7 2640.04
     2102639.332   217.6 2636.99   227.5 2635.81   237.4  2636.5     2452638.089
   296.7 2650.36   306.6 2653.13   316.5 2656.44   336.3 2663.85   346.2 2667.82
     366 2676.14   405.5 2692.46   425.3 2701.01   435.2 2705.43     455 2714.56
#Mann= 3 , 0 , 0
       0      .1       0     210    .045       0     245      .1       0
Bank Sta=210,245
XS Rating Curve= 0 ,0
Exp/Cntr=0.3,0.1

Type RM Length L Ch R = 1 ,8537.2  ,415.3,385.6,409.1
XS GIS Cut Line= 2
     2102649.277      434055.184     2102509.219      434488.091
#Sta/Elev= 30
       0 2658.97     9.9 2654.28    19.8 2652.16    29.7 2651.87    49.5 2652.63
    59.4 2652.36    69.2 2651.41   118.7 2645.61   128.6 2644.04   138.5 2641.77
   168.2 2633.45   187.9 2627.83     2102621.059   217.6 2618.94   227.5 2617.67
   237.4 2618.44     2452620.543   247.3 2621.18   257.2  2624.7   286.8 2633.58
   296.7 2636.41   306.6  2638.8   316.5 2640.41   326.4 2641.81   336.3 2643.88
   346.2 2647.09   356.1 2651.18   405.5 2672.46   435.2 2685.76     455 2694.49
#Mann= 3 , 0 , 0
       0      .1       0     210    .045       0     245      .1       0
Bank Sta=210,245
XS Rating Curve= 0 ,0
Exp/Cntr=0.3,0.1

Type RM Length L Ch R = 1 ,8151.6  ,384,391,398.1
XS GIS Cut Line= 2
     2102272.763      433943.676     2102149.424       434381.64
#Sta/Elev= 30
       0 2682.31    39.6 2653.97    49.5 2647.26    59.4 2641.75    69.2 2638.41
    79.1  2637.1   108.8 2634.37   118.7  2633.7   128.6 2633.44   168.2 2633.69
     178 2632.35   187.9 2628.39   197.8 2622.45   207.7 2615.77     2102614.525
   217.6 2610.41   227.5 2608.35   237.4 2609.95     2452613.151   267.1 2624.12
     277 2628.41   286.8 2631.16   296.7 2631.68   306.6  2631.8   375.9 2632.17
   395.6 2632.89   405.5 2633.55   415.4 2634.76   425.3  2636.5     455 2642.98
#Mann= 3 , 0 , 0
       0      .1       0     210    .045       0     245      .1       0
Bank Sta=210,245
XS Rating Curve= 0 ,0
Exp/Cntr=0.3,0.1

Type RM Length L Ch R = 1 ,7760.5  ,204,213.8,223.6
XS GIS Cut Line= 3
     2101964.488      433855.883     2101838.681      434045.432
     2101712.874      434234.981
#Sta/Elev= 30
       0  2652.4     9.9 2649.06    29.7 2643.21    39.6 2639.91    49.5 2636.12
    69.2  2628.2    79.1 2625.32      89  2623.4    98.9 2622.11   118.7  2620.7
   168.2 2618.55     178 2617.28   187.9 2615.01   197.8 2612.05     2102607.998
   217.6 2605.71   227.5 2604.31   237.4 2604.67     2452605.844   267.1 2610.29
     277 2612.13   286.8 2613.67   296.7 2614.93   316.5 2616.14   326.4 2617.06
   346.2 2620.65   356.1 2622.16   395.6 2626.26   445.1 2632.94     455 2634.44
#Mann= 3 , 0 , 0
       0      .1       0     210    .045       0     245      .1       0
Bank Sta=210,245
XS Rating Curve= 0 ,0
Exp/Cntr=0.3,0.1

Type RM Length L Ch R = 1 ,7546.8  ,242.5,242.6,242.6
XS GIS Cut Line= 2
     2101902.067      433756.098     2101516.417      433997.549
#Sta/Elev= 30
       0 2645.02    19.8 2640.56    29.7 2638.23    39.6 2635.52    49.5 2632.02
    69.2 2624.02    79.1 2620.65      89 2618.53   108.8 2616.11   118.7 2615.11
   128.6 2614.52   138.5 2614.35   168.2 2614.24     178    2614   187.9 2613.03
   197.8 2610.62   207.7 2607.33     2102606.698   217.6 2604.61   227.5 2603.63
   237.4 2604.08     2452604.901     277 2608.61   326.4 2613.94   336.3 2615.46
   346.2 2618.15     366 2625.06   415.4 2641.92   435.2 2648.35     455 2654.52
#Mann= 3 , 0 , 0
       0      .1       0     210    .045       0     245      .1       0
Bank Sta=210,245
XS Rating Curve= 0 ,0
Exp/Cntr=0.3,0.1

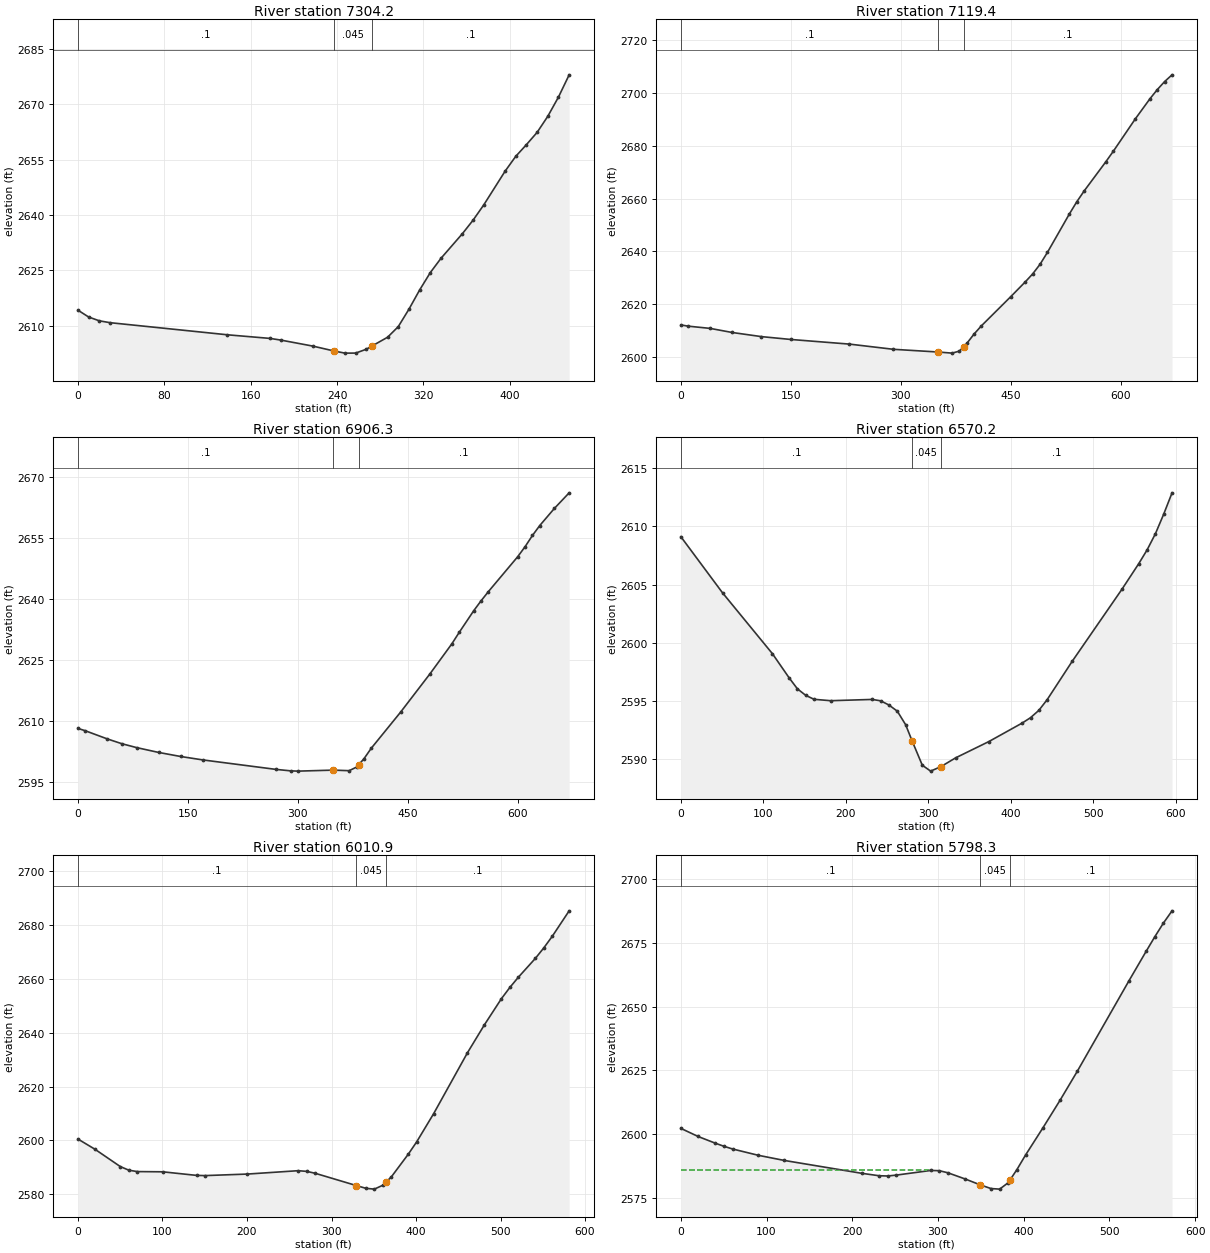
Type RM Length L Ch R = 1 ,7304.2  ,187.3,184.8,182.4
XS GIS Cut Line= 2
     2101777.138      433549.745     2101391.488      433791.196
#Sta/Elev= 29
       0 2614.24     9.9 2612.39    19.8 2611.36    29.7 2610.86   138.5 2607.58
     178  2606.6   187.9 2606.15   217.6 2604.52   237.62603.169   247.3 2602.62
   257.2 2602.63   267.1 2603.67   272.62604.587   286.8 2606.92   296.7 2609.79
   306.6 2614.51   316.5 2619.71   326.4 2624.42   336.3 2628.29   356.1 2634.94
     366  2638.6   375.9 2642.73   395.6 2651.83   405.5 2655.86   415.4 2659.03
   425.3 2662.35   435.2  2666.7   445.1 2671.91     455 2677.93
#Mann= 3 , 0 , 0
       0      .1       0   237.6    .045       0   272.6      .1       0
Bank Sta=237.6,272.6
XS Rating Curve= 0 ,0
Exp/Cntr=0.3,0.1

Type RM Length L Ch R = 1 ,7119.4  ,219,213.1,207.2
XS GIS Cut Line= 2
      2101728.67      433316.459     2101205.911      433735.945
#Sta/Elev= 30
       0 2612.09      10 2611.62      40 2610.77      70 2609.22     110 2607.65
   150.1 2606.57   230.1 2604.81   290.1 2602.84   351.12601.811   370.1 2601.39
   380.2 2602.16   386.12603.877   390.2 2605.07   400.2 2608.66   410.2 2611.76
   450.2 2622.81   470.2 2628.47   480.2 2631.47   490.2  2635.1   500.2 2639.58
   530.2 2654.18   540.2 2658.75   550.2 2662.84   580.2 2674.07   590.2 2677.98
   620.2 2690.25   640.2 2697.89   650.2 2701.35   660.2  2704.4   670.3 2706.95
#Mann= 3 , 0 , 0
       0      .1       0   351.1    .045       0   386.1      .1       0
Bank Sta=351.1,386.1
XS Rating Curve= 0 ,0
Exp/Cntr=0.3,0.1

Type RM Length L Ch R = 1 ,6906.3  ,329.7,336.1,342.6
XS GIS Cut Line= 2
      2101510.31      433100.505     2101111.797      433639.425
#Sta/Elev= 30
       0 2608.14      10 2607.56      40 2605.55      60 2604.36      80 2603.41
     110 2602.22     140 2601.22   170.1 2600.38   270.1 2598.04   290.1 2597.68
   300.1 2597.61   348.22597.856   370.1 2597.72   380.2 2598.61   383.22599.219
   390.2 2600.64   400.2 2603.24   440.2 2612.13   480.2 2621.55   510.2 2628.98
   520.2 2631.79   540.2 2637.18   550.2 2639.61   560.2 2641.88   600.2 2650.48
   610.2 2652.94   620.2 2655.69   630.2 2658.14   650.2 2662.37   670.3  2666.2
#Mann= 3 , 0 , 0
       0      .1       0   348.2    .045       0   383.2      .1       0
Bank Sta=348.2,383.2
XS Rating Curve= 0 ,0
Exp/Cntr=0.3,0.1

Type RM Length L Ch R = 1 ,6570.2  ,560.3,559.3,564.9
XS GIS Cut Line= 2
     2101321.405       432951.18     2100849.006      433313.755
#Sta/Elev= 30
       0 2609.11    50.5 2604.29     111 2599.06   131.2 2596.99   141.3 2596.04
   151.4 2595.48   161.5 2595.14   181.7 2595.02   232.1 2595.13   242.2 2595.01
   252.3 2594.65   262.4 2594.12   272.5 2592.96   280.22591.595   292.7 2589.48
   302.8 2588.97   315.22589.353   333.1 2590.11   373.4 2591.51   413.8  2593.1
   423.9 2593.56     434 2594.19   444.1 2595.11   474.4  2598.4   534.9 2604.61
   555.1 2606.79   565.2 2607.97   575.3 2609.36   585.4 2611.05   595.5 2612.88
#Mann= 3 , 0 , 0
       0      .1       0   280.2    .045       0   315.2      .1       0
Bank Sta=280.2,315.2
XS Rating Curve= 0 ,0
Exp/Cntr=0.3,0.1

Type RM Length L Ch R = 1 ,6010.9  ,207.7,212.6,217.5
XS GIS Cut Line= 2
     2100904.624      432578.169     2100464.424      432957.651
#Sta/Elev= 30
       0 2600.51      20 2596.75    50.1  2590.3    60.1 2588.97    70.1 2588.44
   100.2 2588.36   140.3 2587.03   150.3 2586.95   200.4 2587.52   260.5 2588.77
   270.6 2588.52   280.6 2587.82   329.52583.246   340.7 2582.23   350.7 2581.93
   360.7 2583.37   364.5 2584.54   370.8 2586.48   390.8 2594.88   400.8 2599.48
   420.9 2609.96   460.9 2632.56     481 2642.95     501 2652.59     511 2656.77
   521.1 2660.58   541.1 2667.53   551.1 2671.42   561.2 2675.76   581.2 2685.22
#Mann= 3 , 0 , 0
       0      .1       0   329.5    .045       0   364.5      .1       0
#XS Ineff= 2 , 0
          259.88 2588.53
Permanent Ineff=
       F       F
Bank Sta=329.5,364.5
XS Rating Curve= 0 ,0
Exp/Cntr=0.3,0.1

Type RM Length L Ch R = 1 ,5798.3  ,142.3,144.1,145.9
XS GIS Cut Line= 2
      2100845.91       432462.18     2100338.921      432729.336
#Sta/Elev= 30
       0 2602.28    20.1  2599.1    40.2 2596.47    50.3 2595.25    60.3  2594.2
    90.5 2591.71   120.6 2589.71   211.1 2584.66   231.2 2583.71   241.3 2583.61
   251.4 2583.96   291.6 2585.78   301.6 2585.69   311.7 2584.85   331.8 2582.43
   349.42580.116   361.9 2578.68     372 2578.46     382    2581   384.42582.219
   392.1 2586.13   402.2 2591.84   422.3 2602.41   442.4 2613.28   462.5 2624.64
   522.8 2660.12   542.9 2671.71     553 2677.41     563 2682.76   573.1 2687.57
#Mann= 3 , 0 , 0
       0      .1       0   349.4    .045       0   384.4      .1       0
#XS Ineff= 2 , 0
          292.29 2585.97
Permanent Ineff=
       F       F
Bank Sta=349.4,384.4
XS Rating Curve= 0 ,0
Exp/Cntr=0.3,0.1

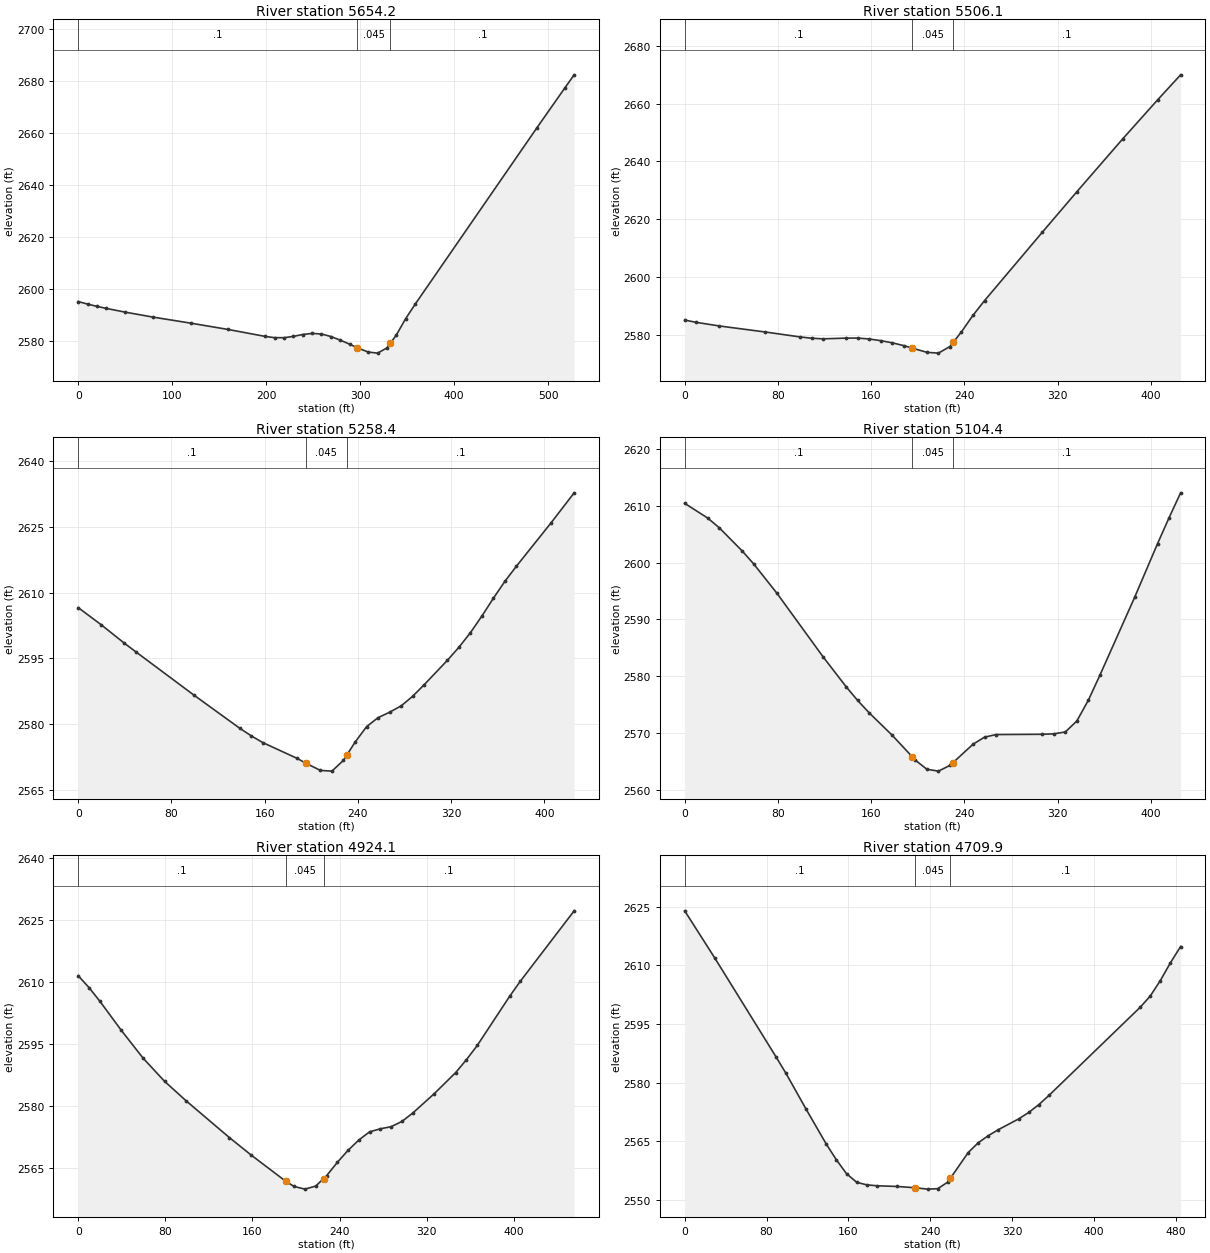
Type RM Length L Ch R = 1 ,5654.2  ,208.6,148.1,189.2
XS GIS Cut Line= 2
     2100751.798      432377.176      2100267.06      432585.909
#Sta/Elev= 29
       0 2595.21      10 2594.22    19.9 2593.36    29.9 2592.57    49.8 2591.15
    79.7 2589.22   119.5 2586.92   159.3 2584.49   199.2 2581.79   209.1 2581.32
   219.1 2581.31     229 2581.82     239 2582.54     249 2582.96   258.9 2582.73
   268.9 2581.77   278.8 2580.38   288.8 2578.83   297.22577.405   308.7 2575.79
   318.6 2575.38   328.6 2577.39   332.22579.183   338.6 2582.37   348.5 2588.64
   358.5 2594.14   487.9 2661.86   517.8 2677.28   527.8 2682.36
#Mann= 3 , 0 , 0
       0      .1       0   297.2    .045       0   332.2      .1       0
#XS Ineff= 2 , 0
          250.84 2582.84
Permanent Ineff=
       F       F
Bank Sta=297.2,332.2
XS Rating Curve= 0 ,0
Exp/Cntr=0.3,0.1

Type RM Length L Ch R = 1 ,5506.1  ,247.8,247.7,251.1
XS GIS Cut Line= 2
     2100608.287      432288.485     2100210.335      432439.182
#Sta/Elev= 26
       0 2585.05     9.9 2584.25    29.7    2583    69.3  2580.9      99  2579.2
   108.9 2578.75   118.8 2578.54   138.5 2578.79   148.4 2578.81   158.3 2578.49
   168.2 2577.91   178.1 2577.17     188 2576.18   195.32575.325   207.8 2573.87
   217.7 2573.59   227.6 2575.88   230.32577.271   237.5 2580.98   247.4 2586.71
   257.3 2591.79   306.8 2615.44   336.5  2629.5     376 2647.88   405.7 2661.28
   425.5 2669.98
#Mann= 3 , 0 , 0
       0      .1       0   195.3    .045       0   230.3      .1       0
Bank Sta=195.3,230.3
XS Rating Curve= 0 ,0
Exp/Cntr=0.3,0.1

Type RM Length L Ch R = 1 ,5258.4  ,154,154,154
XS GIS Cut Line= 2
     2100549.824       432049.74     2100151.872      432200.436
#Sta/Elev= 30
       0 2606.55    19.8 2602.62    39.6 2598.42    49.5 2596.44      99 2586.62
   138.5 2579.01   148.4 2577.27   158.3 2575.73     188 2572.09   195.32571.006
   207.8 2569.36   217.7  2569.2   227.6 2571.68   230.32572.804   237.5  2575.8
   247.4 2579.36   257.3 2581.42   267.2 2582.66   277.1 2584.11     287 2586.31
   296.9 2588.96   316.7  2594.5   326.6 2597.48   336.5 2600.82   346.4 2604.65
   356.3 2608.73   366.2  2612.6     376 2616.02   405.7 2625.92   425.5 2632.77
#Mann= 3 , 0 , 0
       0      .1       0   195.3    .045       0   230.3      .1       0
Bank Sta=195.3,230.3
XS Rating Curve= 0 ,0
Exp/Cntr=0.3,0.1

Type RM Length L Ch R = 1 ,5104.4  ,182.4,180.3,178
XS GIS Cut Line= 2
     2100480.539      431912.303     2100082.587      432062.999
#Sta/Elev= 30
       0 2610.44    19.8 2607.84    29.7 2606.13    49.5 2602.02    59.4 2599.72
    79.2 2594.59   118.8 2583.39   138.5 2578.14   148.4 2575.72   158.3 2573.54
   178.1 2569.58   195.32565.788   197.9  2565.2   207.8  2563.6   217.7 2563.27
   227.6 2564.28   230.32564.784   247.4 2568.01   257.3 2569.26   267.2 2569.71
   306.8 2569.76   316.7 2569.84   326.6 2570.17   336.5 2572.11   346.4 2575.79
   356.3 2580.19     386 2593.86   405.7 2603.34   415.6 2607.91   425.5 2612.29
#Mann= 3 , 0 , 0
       0      .1       0   195.3    .045       0   230.3      .1       0
Bank Sta=195.3,230.3
XS Rating Curve= 0 ,0
Exp/Cntr=0.3,0.1

Type RM Length L Ch R = 1 ,4924.1  ,213.4,214.2,215.1
XS GIS Cut Line= 3
     2100380.551      431739.269      2100175.59      431839.114
     2099977.411      431950.658
#Sta/Elev= 30
       0 2611.44     9.9 2608.58    19.8  2605.3    39.6 2598.22    59.5 2591.52
    79.3 2585.89    99.1 2581.17   138.8 2572.28   158.6 2568.09   190.42561.734
   198.2 2560.45   208.2  2559.8   218.1 2560.54   225.42562.369     228 2563.02
   237.9 2566.27   247.8 2569.19   257.6 2571.67   267.5 2573.66   277.4  2574.4
   287.3 2574.91   297.2 2576.17   307.1 2578.19   326.9 2582.89   346.6    2588
   356.5 2591.13   366.4 2594.56   396.1 2606.44     406 2610.12   455.4 2627.15
#Mann= 3 , 0 , 0
       0      .1       0   190.4    .045       0   225.4      .1       0
Bank Sta=190.4,225.4
XS Rating Curve= 0 ,0
Exp/Cntr=0.3,0.1

Type RM Length L Ch R = 1 ,4709.9  ,300.8,287.5,274.3
XS GIS Cut Line= 2
     2100324.785      431538.028     2099881.665      431734.868
#Sta/Elev= 30
       0 2623.94    29.7 2611.77    89.1  2586.7      99 2582.42   118.7 2573.25
   138.5 2564.29   148.4 2560.27   158.3 2556.73   168.2 2554.55   178.1 2553.89
     188 2553.66   207.8 2553.48   224.92553.163   237.5  2552.8   247.4 2552.91
   257.3 2554.61   259.92555.608   277.1 2562.12     287 2564.65   296.9 2566.47
   306.8 2568.02   326.6 2570.76   336.4  2572.4   346.3 2574.41   356.2 2576.76
   445.3 2599.27   455.2 2602.15   465.1 2606.13     475 2610.69   484.9 2614.82
#Mann= 3 , 0 , 0
       0      .1       0   224.9    .045       0   259.9      .1       0
Bank Sta=224.9,259.9
XS Rating Curve= 0 ,0
Exp/Cntr=0.3,0.1

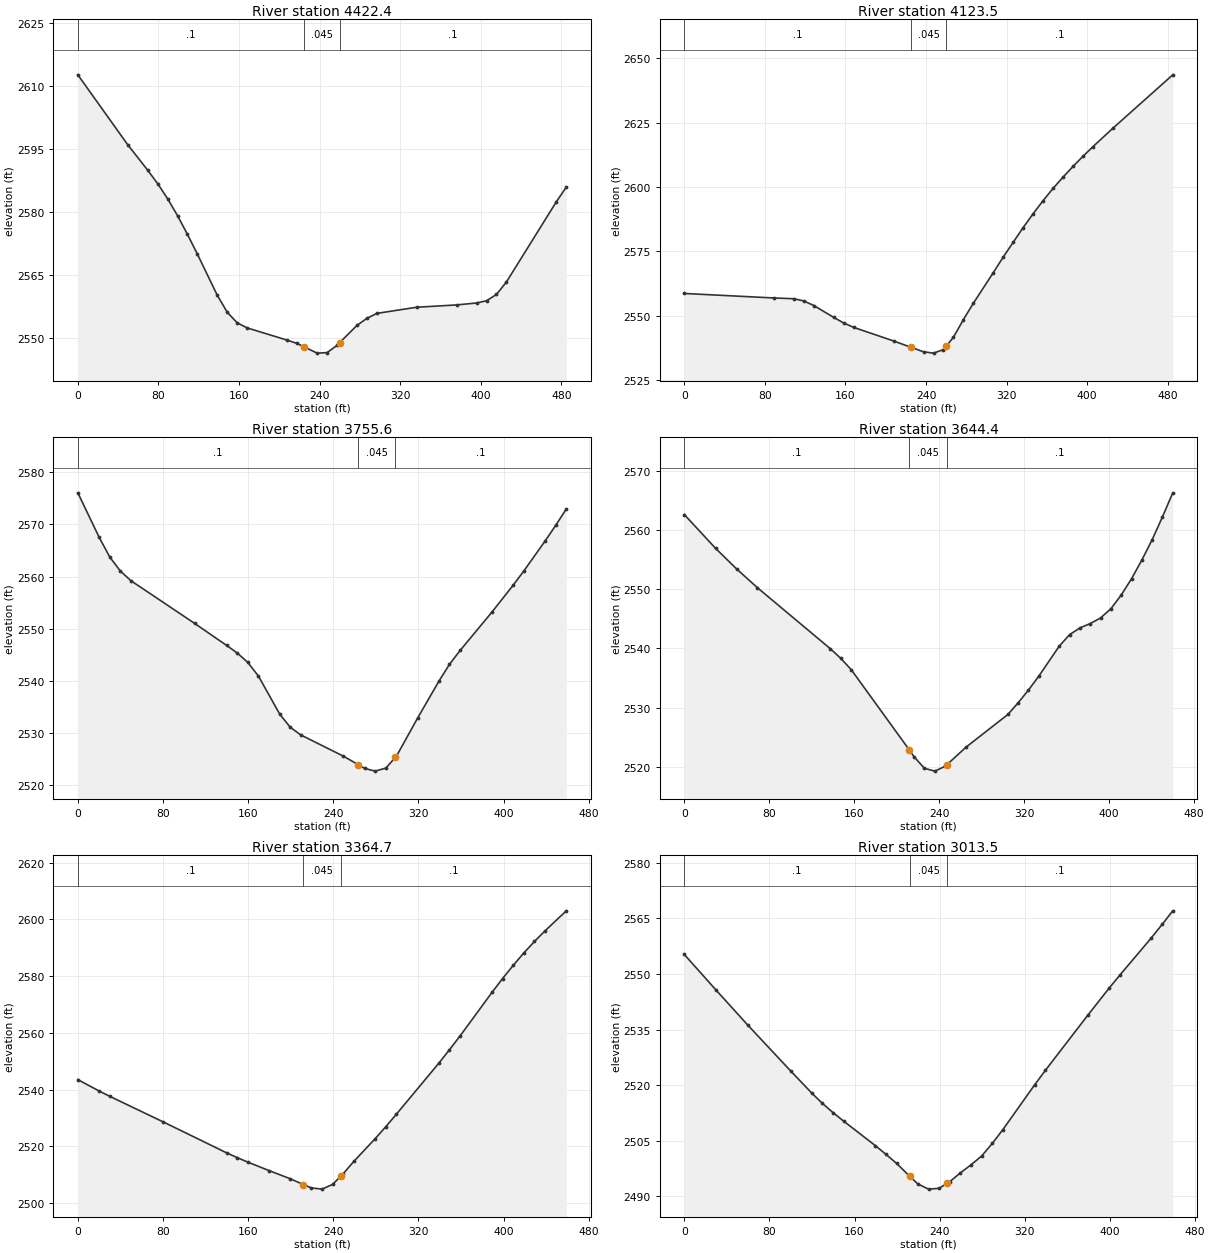
Type RM Length L Ch R = 1 ,4422.4  ,301.2,298.9,296.6
XS GIS Cut Line= 2
     2100096.215      431182.329     2099835.673      431591.253
#Sta/Elev= 30
       0  2612.6    49.5 2595.99    69.3 2589.94    79.2 2586.74    89.1 2583.15
      99  2579.1   108.8 2574.68   118.7 2569.96   138.5 2560.15   148.4 2556.12
   158.3 2553.62   168.2 2552.42   207.8 2549.52   217.7 2548.72   224.92547.891
   237.5 2546.43   247.4 2546.55   257.3 2548.27   259.92548.916   277.1 2553.03
     287 2554.71   296.9 2555.88   336.4 2557.34     376 2557.89   395.8 2558.35
   405.7 2558.88   415.6 2560.38   425.5 2563.36     475  2582.4   484.9  2585.9
#Mann= 3 , 0 , 0
       0      .1       0   224.9    .045       0   259.9      .1       0
Bank Sta=224.9,259.9
XS Rating Curve= 0 ,0
Exp/Cntr=0.3,0.1

Type RM Length L Ch R = 1 ,4123.5  ,356.9,368,379.7
XS GIS Cut Line= 2
     2099791.509      431174.159     2099577.151      431609.075
#Sta/Elev= 30
       0 2558.57    89.1 2556.81   108.8 2556.52   118.7 2555.64   128.6 2553.88
   148.4 2549.24   158.3 2547.07   168.2 2545.37   207.8  2540.1   224.92537.651
   237.5 2535.88   247.4 2535.37   257.3 2536.75   259.92538.013   267.2 2541.56
   277.1 2548.42     287  2554.8   306.8  2566.7   316.6 2572.71   326.6 2578.54
   336.4 2584.19   346.3 2589.56   356.2 2594.68   366.1 2599.43     376 2603.81
   385.9 2607.96   395.8 2611.91   405.7 2615.65   425.5 2622.82   484.9 2643.58
#Mann= 3 , 0 , 0
       0      .1       0   224.9    .045       0   259.9      .1       0
Bank Sta=224.9,259.9
XS Rating Curve= 0 ,0
Exp/Cntr=0.3,0.1

Type RM Length L Ch R = 1 ,3755.6  ,116.5,111.1,113.9
XS GIS Cut Line= 2
     2099692.896      430937.338     2099322.824      431208.869
#Sta/Elev= 30
       0 2576.04      20 2567.54    29.9 2563.78    39.9 2561.07    49.9 2559.21
   109.8 2551.03   139.7 2546.84   149.7 2545.38   159.6 2543.59   169.6 2540.99
   189.6  2533.7   199.6 2531.15   209.5 2529.68   249.5 2525.62   263.52523.982
   269.4 2523.28   279.4 2522.75   289.4 2523.33   298.52525.405   299.4 2525.61
   319.3 2532.92   339.3 2539.97   349.2 2543.19   359.2 2545.85   389.2 2553.22
   409.1 2558.36   419.1 2561.07     439 2566.79     449 2569.79     459 2572.95
#Mann= 3 , 0 , 0
       0      .1       0   263.5    .045       0   298.5      .1       0
Bank Sta=263.5,298.5
XS Rating Curve= 0 ,0
Exp/Cntr=0.3,0.1

Type RM Length L Ch R = 1 ,3644.4  ,301.4,279.7,257.8
XS GIS Cut Line= 3
     2099613.125      430869.066     2099363.722      431044.155
     2099317.146      431192.235
#Sta/Elev= 30
       0  2562.6    29.5 2556.88    49.2 2553.42    68.8 2550.25   137.6 2539.92
   147.4  2538.3   157.3 2536.37     2122522.808   216.3  2521.7   226.1 2519.73
   235.9 2519.25   245.8 2520.08     2472520.286   265.4 2523.31   304.7 2528.82
   314.4 2530.79   324.1 2532.94   333.8 2535.28   353.2 2540.39   362.9 2542.32
   372.6 2543.45   382.3 2544.18     392 2545.13   401.8  2546.7   411.4 2548.98
   421.2 2551.76   430.8 2554.88   440.6 2558.35   450.3  2562.2     460 2566.27
#Mann= 3 , 0 , 0
       0      .1       0     212    .045       0     247      .1       0
Bank Sta=212,247
XS Rating Curve= 0 ,0
Exp/Cntr=0.3,0.1

Type RM Length L Ch R = 1 ,3364.7  ,341.1,351.2,361.3
XS GIS Cut Line= 2
     2099163.728      430767.944     2099144.492      431226.542
#Sta/Elev= 29
       0 2543.55      20 2539.53    29.9 2537.67    79.8 2528.72   139.7 2517.76
   149.7 2516.07   159.6  2514.5   179.6  2511.5   199.6 2508.62     212 2506.56
   219.5 2505.39   229.5 2504.96   239.5 2506.65     2472509.492   249.5 2510.44
   259.4 2514.75   279.4 2522.74   289.4 2526.96   299.4 2531.39   339.3 2549.37
   349.2 2554.05   359.2 2558.94   389.2 2574.28   399.1 2579.16   409.1 2583.79
   419.1 2588.18   429.1 2592.23     439 2595.96     459 2603.02
#Mann= 3 , 0 , 0
       0      .1       0     212    .045       0     247      .1       0
Bank Sta=212,247
XS Rating Curve= 0 ,0
Exp/Cntr=0.3,0.1

Type RM Length L Ch R = 1 ,3013.5  ,426.9,420,413.2
XS GIS Cut Line= 2
     2098951.114      430651.005     2098736.006      431056.481
#Sta/Elev= 30
       0 2555.28    29.9 2545.64    59.9 2536.13    99.8 2523.87   119.7 2517.88
   129.7 2515.09   139.7 2512.59   149.7 2510.29   179.6 2503.65   189.6 2501.29
   199.6 2498.84     2122495.337   219.5 2493.32   229.5 2491.92   239.5 2492.14
     247 2493.49   249.5 2493.94   259.4  2496.3   269.4 2498.47   279.4 2500.86
   289.4 2504.25   299.4    2508   329.3 2520.11   339.3 2523.99   379.2 2538.88
   399.1 2546.15   409.1 2549.64     439  2559.8     449 2563.38     459 2567.06
#Mann= 3 , 0 , 0
       0      .1       0     212    .045       0     247      .1       0
Bank Sta=212,247
XS Rating Curve= 0 ,0
Exp/Cntr=0.3,0.1

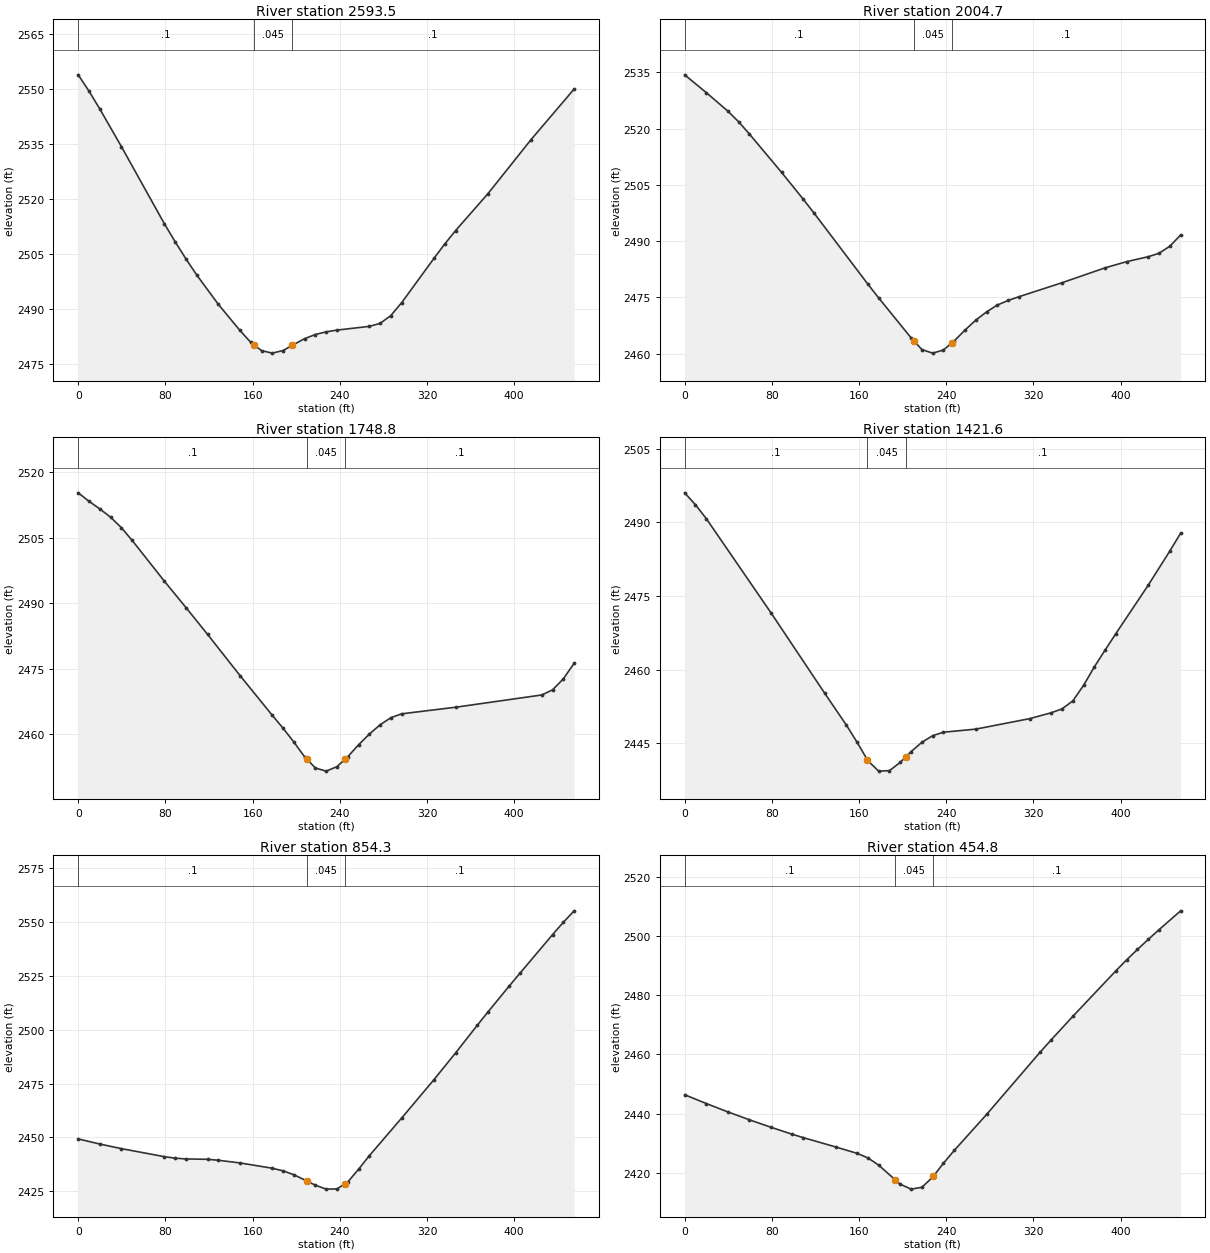
Type RM Length L Ch R = 1 ,2593.5  ,588.7,588.7,588.7
XS GIS Cut Line= 2
     2098496.523      430539.208     2098413.883       430986.64
#Sta/Elev= 30
       0  2553.8     9.9 2549.36    19.8 2544.51    39.6 2534.27    79.1 2513.22
      89  2508.3    98.9 2503.65   108.8 2499.26   128.6 2491.28   148.4 2484.18
   158.3 2480.95   161.22480.291   168.2  2478.7     178 2478.01   187.9 2478.71
   196.2 2480.11   207.7 2481.95   217.6 2483.08   227.5 2483.81   237.4 2484.28
   267.1  2485.3     277 2486.11   286.8 2488.24   296.7 2491.73   326.4 2503.82
   336.3 2507.74   346.2 2511.38   375.9 2521.43   415.4 2536.14     455 2549.94
#Mann= 3 , 0 , 0
       0      .1       0   161.2    .045       0   196.2      .1       0
Bank Sta=161.2,196.2
XS Rating Curve= 0 ,0
Exp/Cntr=0.3,0.1

Type RM Length L Ch R = 1 ,2004.7  ,255.4,255.9,256.5
XS GIS Cut Line= 3
     2097954.683      430331.707     2097913.363      430555.423
     2097872.043      430779.139
#Sta/Elev= 30
       0 2534.36    19.8 2529.62    39.6 2524.69    49.5 2521.83    59.4 2518.57
      89 2508.31   108.8 2501.17   118.7 2497.48   168.2 2478.48     178 2474.85
   207.7 2464.21     2102463.485   217.6 2461.09   227.5 2460.13   237.4 2460.96
     245 2462.81   247.3 2463.37   257.2 2466.29   267.1 2468.92     277 2471.14
   286.8 2472.95   296.7 2474.17   306.6 2475.17   346.2 2478.91   385.8 2482.89
   405.5 2484.53   425.3 2485.85   435.2 2486.76   445.1 2488.65     455 2491.63
#Mann= 3 , 0 , 0
       0      .1       0     210    .045       0     245      .1       0
Bank Sta=210,245
XS Rating Curve= 0 ,0
Exp/Cntr=0.3,0.1

Type RM Length L Ch R = 1 ,1748.8  ,338,327.3,316.5
XS GIS Cut Line= 3
     2097714.941      430263.702     2097668.101      430486.328
     2097621.261      430708.954
#Sta/Elev= 30
       0 2515.34     9.9  2513.4    19.8 2511.66    29.7 2509.76    39.6 2507.35
    49.5 2504.44    79.1 2495.08    98.9 2489.04   118.7  2482.9   148.4 2473.48
     178 2464.38   187.9 2461.41   197.8 2458.25   207.7 2454.85     2102454.253
   217.6 2452.28   227.5 2451.57   237.4  2452.6     245 2454.35   247.3 2454.88
   257.2  2457.6   267.1 2460.06     277 2462.19   286.8 2463.81   296.7  2464.7
   346.2 2466.21   425.3 2469.02   435.2  2470.2   445.1 2472.71     455 2476.31
#Mann= 3 , 0 , 0
       0      .1       0     210    .045       0     245      .1       0
Bank Sta=210,245
XS Rating Curve= 0 ,0
Exp/Cntr=0.3,0.1

Type RM Length L Ch R = 1 ,1421.6  ,575.7,567.3,563.8
XS GIS Cut Line= 2
     2097302.072      430301.341      2097411.21      430743.058
#Sta/Elev= 29
       0 2495.98     9.9 2493.55    19.8 2490.74    79.1 2471.59   128.6 2455.15
   148.4 2448.69   158.3 2445.17   167.72441.609   168.2 2441.42     178 2439.34
   187.9 2439.44   197.8 2441.13   202.72442.209   207.7 2443.31   217.6  2445.2
   227.5 2446.56   237.4 2447.26   267.1 2447.89   316.5 2450.02   336.3 2451.22
   346.2 2452.01   356.1 2453.63     366 2456.81   375.9 2460.58   385.8    2464
   395.6 2467.33   425.3 2477.19   445.1 2484.14     455 2487.76
#Mann= 3 , 0 , 0
       0      .1       0   167.7    .045       0   202.7      .1       0
Bank Sta=167.7,202.7
XS Rating Curve= 0 ,0
Exp/Cntr=0.3,0.1

Type RM Length L Ch R = 1 ,854.3   ,393.8,399.4,405
XS GIS Cut Line= 2
     2096887.123      430646.217     2097074.662      431060.771
#Sta/Elev= 30
       0 2449.31    19.8 2446.93    39.6  2444.8    79.1 2441.06      89 2440.37
    98.9    2440   118.7 2439.84   128.6 2439.39   148.4 2438.16     178  2435.7
   187.9 2434.49   197.8 2432.68     2102429.719   217.6  2427.8   227.5 2425.99
   237.4 2426.09     2452428.539   247.3 2429.28   257.2 2435.23   267.1 2441.52
   296.7 2458.97   326.4 2476.84   346.2 2489.23     366    2502   375.9 2508.25
   395.6 2520.41   405.5 2526.39   435.2 2544.18   445.1 2549.93     455 2555.23
#Mann= 3 , 0 , 0
       0      .1       0     210    .045       0     245      .1       0
Bank Sta=210,245
XS Rating Curve= 0 ,0
Exp/Cntr=0.3,0.1

Type RM Length L Ch R = 1 ,454.8   ,426.9,426.9,426.9
XS GIS Cut Line= 3
     2096564.952       430761.65     2096604.767      430985.639
     2096644.583      431209.628
#Sta/Elev= 29
       0 2446.38    19.8 2443.42    39.6 2440.59    59.4 2437.92    79.1 2435.41
    98.9 2433.01   108.8  2431.9   138.5 2428.76   158.3 2426.58   168.2 2425.04
     178  2422.6   193.22417.639   197.8 2416.18   207.7 2414.51   217.6 2415.12
   227.5 2418.55   228.22418.882   237.4 2423.25   247.3 2427.57     277 2439.73
   326.4 2460.88   336.3 2464.94   356.1 2472.85   395.6 2488.23   405.5 2491.94
   415.4 2495.45   425.3 2498.83   435.2 2502.12     455 2508.49
#Mann= 3 , 0 , 0
       0      .1       0   193.2    .045       0   228.2      .1       0
Bank Sta=193.2,228.2
XS Rating Curve= 0 ,0
Exp/Cntr=0.3,0.1

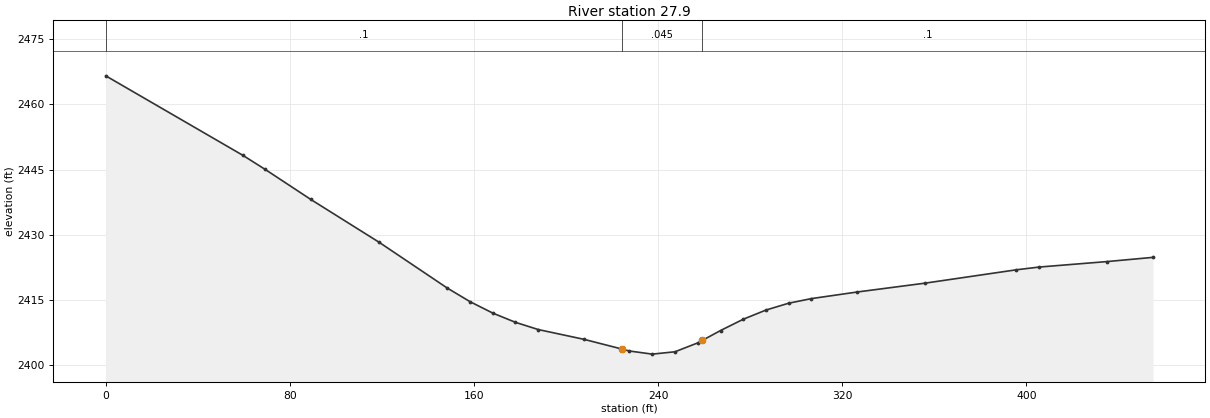
Type RM Length L Ch R = 1 ,27.9    ,28.1,27.9,27.7
XS GIS Cut Line= 2
     2096149.959      430841.243     2096229.589      431289.221
#Sta/Elev= 28
       0 2466.59    59.4 2448.36    69.2 2445.09      89 2438.19   118.7 2428.34
   148.4 2417.78   158.3 2414.65   168.2 2412.02     178 2409.91   187.9 2408.25
   207.7 2406.01   224.22403.777   227.5 2403.32   237.4  2402.6   247.3 2403.14
   257.2 2405.19   259.22405.764   267.1 2408.03     277 2410.63   286.8 2412.73
   296.7 2414.31   306.6 2415.37   326.4 2416.88   356.1 2418.93   395.6 2421.99
   405.5 2422.62   435.2 2423.89     455 2424.85
#Mann= 3 , 0 , 0
       0      .1       0   224.2    .045       0   259.2      .1       0
Bank Sta=224.2,259.2
XS Rating Curve= 0 ,0
Exp/Cntr=0.3,0.1

Chan Stop Cuts=-1
Use User Specified Reach Order=0